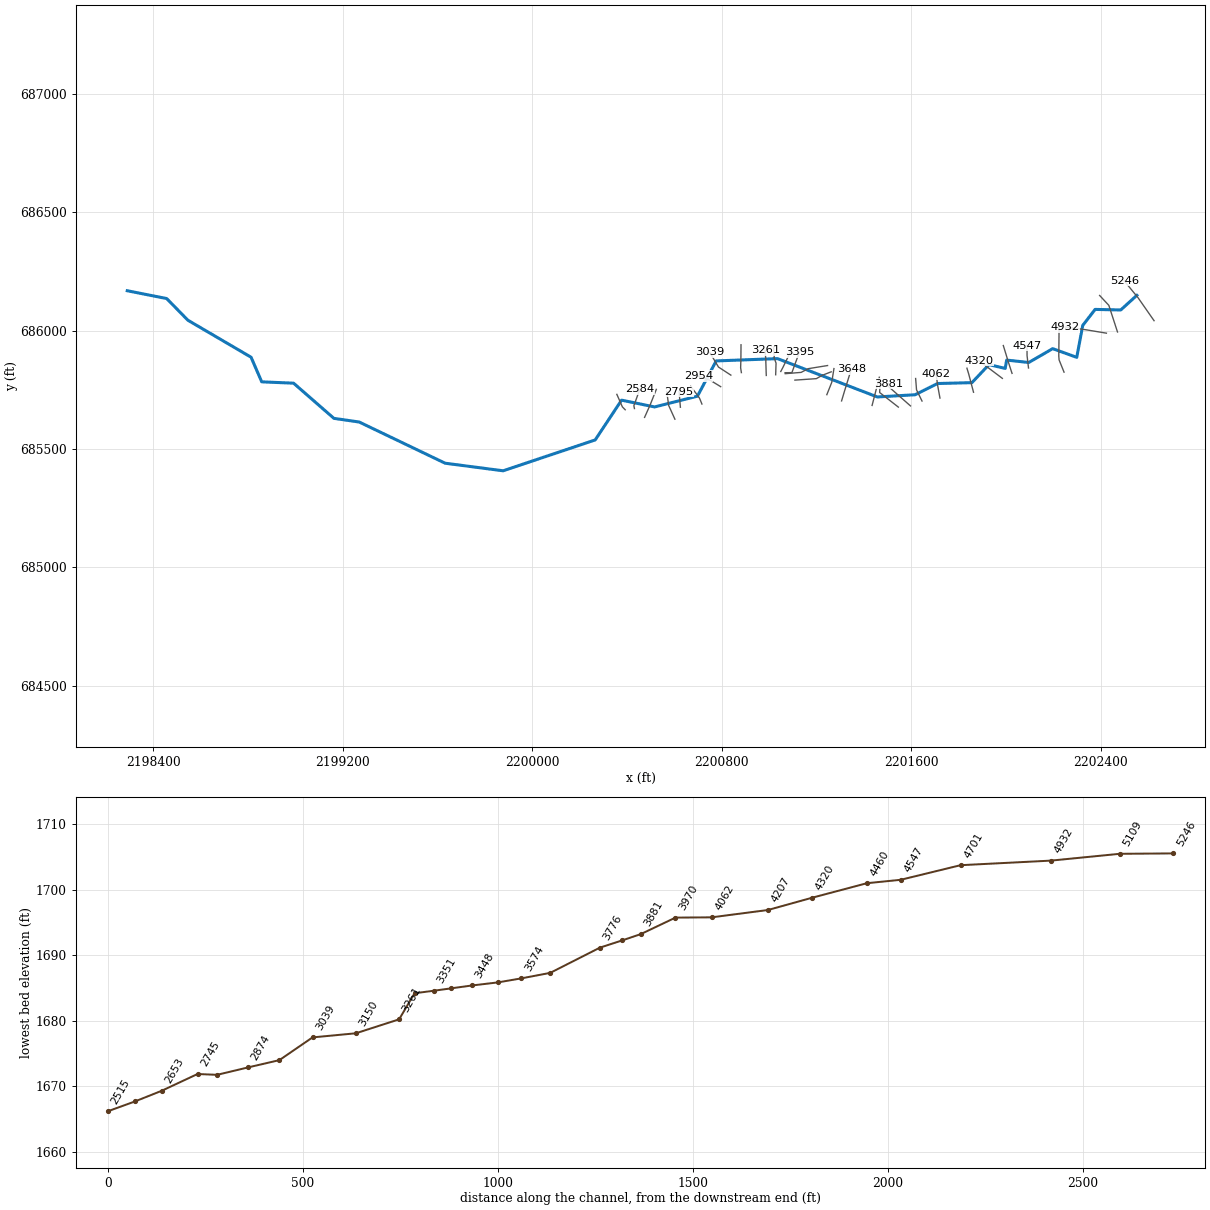
--- LAURELRN5.prj (project) ---

Proj Title=LAURELRN5
Current Plan=p01
Default Exp/Contr=0,0
English Units
Geom File=g01
Flow File=f01
Plan File=p01
BEGIN DESCRIPTION:
-------- MODELED AS PART OF WVEMD CTP PROGRAM, 2023----------
Stream Name: Laurel Run (V)
Flood Zone:  AFH
Upshur County, WV
HEC-RAS Version: RAS 6.3
Vertical Datum: NAVD88
Projection: NAD 1983 StatePlane West Virginia S FIPS 4702 (US Feet)
Terrain: 1-meter LIDAR (FEMA Region III 3DEP collected 2016-2018)
Land Use: 2019 NLCD
Hydrologic Method:
WV SIR2010-5033 regression equations
Additional Model Notes:
None
END DESCRIPTION:
DSS Export Rating Curves= 0
DSS Export Rating Curve Sorted= 0
DSS Export Volume Flow Curves= 0
DXF OffsetX= 0
DXF OffsetY= 0
DXF ScaleX= 0
DXF ScaleY= 0

--- LAURELRN5.p01 (plan) ---

Plan Title=Floodplain
Program Version=6.31
Short Identifier=Floodplain
Geom File=g01
Flow File=f01
Subcritical Flow
K Sum by GR= 0
Std Step Tol= 0.01
Critical Tol= 0.01
Num of Std Step Trials= 20
Max Error Tol= 0.3
Flow Tol Ratio= 0.001
Split Flow NTrial= 30
Split Flow Tol= 0.02
Split Flow Ratio= 0.02
Log Output Level= 0
Friction Slope Method= 1
Unsteady Friction Slope Method= 2
Unsteady Bridges Friction Slope Method= 1
Parabolic Critical Depth
Global Vel Dist= 0 , 0 , 0
Global Log Level= 0
CheckData=True
Encroach Param=-1 ,0,0, 0
Mapping Interval=1HOUR
Computation Time Step Use Courant=        0
Computation Time Step Use Time Series=    0
Computation Time Step Count To Double=0
Computation Time Step Max Doubling=0
Computation Time Step Max Halving=0
Computation Time Step Residence Courant=0
Run HTab= 0
Run UNet= 0
Run Sediment= 0
Run PostProcess= 0
Run WQNet= 0
Run RASMapper=-1
UNET Theta= 0
UNET Theta Warmup= 0
UNET ZTol= 0
UNET ZSATol= 0
UNET MxIter= 0
UNET Max Iter WO Improvement= 0
UNET MaxInSteps= 0
UNET DtIC= 0
UNET DtMin= 0
UNET MaxCRTS= 0
UNET WFStab= 0
UNET SFStab= 0
UNET WFX= 1
UNET SFX= 1
UNET Gravity=32.17405
UNET 1D Methodology=Finite Difference
UNET DSS MLevel= 1
UNET Pardiso=0
UNET DZMax Abort= 0
UNET Use Existing IB Tables= 0
UNET Froude Reduction=False
UNET Froude Limit= 0
UNET Froude Power= 0
UNET D1 Cores= 0
UNET WindReference=Eulerian
UNET WindDragFormulation=Hsu (1988)
UNET D2 Coriolis=0
UNET D2 Cores= 0
UNET D2 Theta= 1
UNET D2 Theta Warmup= 1
UNET D2 Z Tol= 0.01
UNET D2 Volume Tol= 0.01
UNET D2 Max Iterations= 20
UNET D2 Equation= 0
UNET D2 RampUpFraction=0.1
UNET D2 TimeSlices= 1
UNET D2 Turbulence Formulation=Non-Conservative (original)
UNET D2 Eddy Viscosity=0.3
UNET D2 Transverse Eddy Viscosity=0.1
UNET D2 Smagorinsky Mixing=0
UNET D2 BCVolumeCheck=0
UNET D2 Cores=0
UNET D2 SolverType=PARDISO (Direct)
UNET D2 Minimum Iterations= 3
UNET D2 Maximum Iterations= 30
UNET D2 Restart Number= 10
UNET D2 Relaxation Coeff=1.3
UNET D2 SOR Precondition Iterations= 10
UNET D2 ILUT Maximum Fill= 8
UNET D2 ILUT Tolerance=1E-08
UNET D2 Convergence Tolerance=0.00001
UNET D1D2 MaxIter= 0
UNET D1D2 ZTol=0.01
UNET D1D2 QTol=0.1
UNET D1D2 MinQTol=1
Write IC File= 0
Write IC File at Fixed DateTime=0
Write IC File at Sim End=0
Echo Input=False
Echo Parameters=False
Echo Output=False
Write Detailed= 0
HDF Write Warmup=0
HDF Write Time Slices=0
HDF Flush=0
HDF Compression= 1
HDF Chunk Size= 1
HDF Spatial Parts= 1
HDF Use Max Rows=0
HDF Fixed Rows= 1
Calibration Method= 0
Calibration Iterations= 20
Calibration Max Change=0.05
Calibration Tolerance=0.2
Calibration Maximum=1.5
Calibration Minimum=0.5
Calibration Optimization Method= 1
WQ AD Non Conservative
WQ ULTIMATE=-1
WQ Max Comp Step=1HOUR
WQ Output Interval=15MIN
WQ Output Selected Increments= 0
WQ Create Restart=0
WQ Fixed Restart=0
WQ System Summary=0
WQ Write To DSS=0
Sorting and Armoring Iterations= 10
XS Update Threshold= 0.02
Bed Roughness Predictor= 0
Hydraulics Update Threshold= 0.02
Energy Slope Method= 1
Volume Change Method= 1
Sediment Retention Method= 0
Sediment TS Multiplier= 1
Warm Up Method= 0
XS Weighting Method= 0
Number of US Weighted Cross Sections= 1
Number of DS Weighted Cross Sections= 1
Upstream XS Weight=0
Main XS Weight=1
Downstream XS Weight=0
Number of DS XS's Weighted with US Boundary= 1
Upstream Boundary Weight= 1
Weight of XSs Associated with US Boundary= 0
Number of US XS's Weighted with DS Boundary= 1
Downstream Boundary Weight= 0.5
Weight of XSs Associated with DS Boundary= 0.5
Percentile Method= 0
Sediment Output Level= 3
Mass or Volume Output= 0
Output Increment Type= 1
Profile and TS Output Increment= 1
Transport Output Increment 1
XS Output Flag= 0
XS Output Increment= 10
Read HDF5 Sediment Hotstart= 0
Sediment Hotstart Type= 0
Write Gradation File= 0
Read Gradation Hotstart= 0
Write HDF5 File= 1
Write Binary Output= 1
Write DSS Sediment File= 0
DSS Sediment Output Type= 1
SV Curve= 0
Specific Gage Flag= 0
Subcell Erosion Methods= 0
Subcell Deposition Methods= 0
Advection Scheme= 1
Matrix Solver= 0
Implicit Weighting Factor= 1
Maximum Outer Loop Convergence Iterations= 5
Convergence Maximum Absolute= 0.001
Convergence RMSE= 0.0001
Grain Fractions Max Abs Error= 0.001
Max Subgrid Regions= 1
Max Subgrid Length Scale= 3.402823E+38
Initial Layer Thickness= 3.402823E+38
Min Layer Thickness= 3.402823E+38
Max Layer Thickness= 3.402823E+38
Number of Layers= 5

--- LAURELRN5.f01 (steady flow) ---

Flow Title=Flows
Program Version=6.30
Number of Profiles= 1
Profile Names=01pct
River Rch & RM=LAURELRN5,Main            ,5246
     371
Boundary for River Rch & Prof#=LAURELRN5,Main            , 1
Up Type= 0
Dn Type= 3
Dn Slope=0.04806
DSS Import GetInterval= 0
DSS Import GetPeak= 0
DSS Import FillOption= 0

--- LAURELRN5.g01 (geometry) ---

Geom Title=Geometry
Program Version=6.31

River Reach=LAURELRN5       ,Main
Reach XY= 30
     2202553.262      686148.748     2202485.126       686086.85
     2202376.899      686089.225     2202324.589      686021.605
     2202299.349      685886.793     2202197.675      685923.479
      2202096.63      685865.016     2202003.255      685875.261
2201997.16109026 685840.01480744     2201928.795      685856.059
     2201856.625       685779.94     2201711.482      685776.219
2201616.47470792685728.834584162     2201457.111      685719.502
 2201035.6138234685881.358294328     2200776.442      685871.741
     2200697.403       685722.85     2200516.319      685677.321
     2200376.929      685705.966     2200265.525      685537.931
     2199876.714       685407.64     2199631.815      685439.662
     2199268.759      685613.678     2199162.048      685629.074
     2198991.724       685777.65     2198857.112      685783.316
     2198812.213      685887.251     2198545.308      686043.582
     2198455.796      686135.069     2198289.249      686168.064

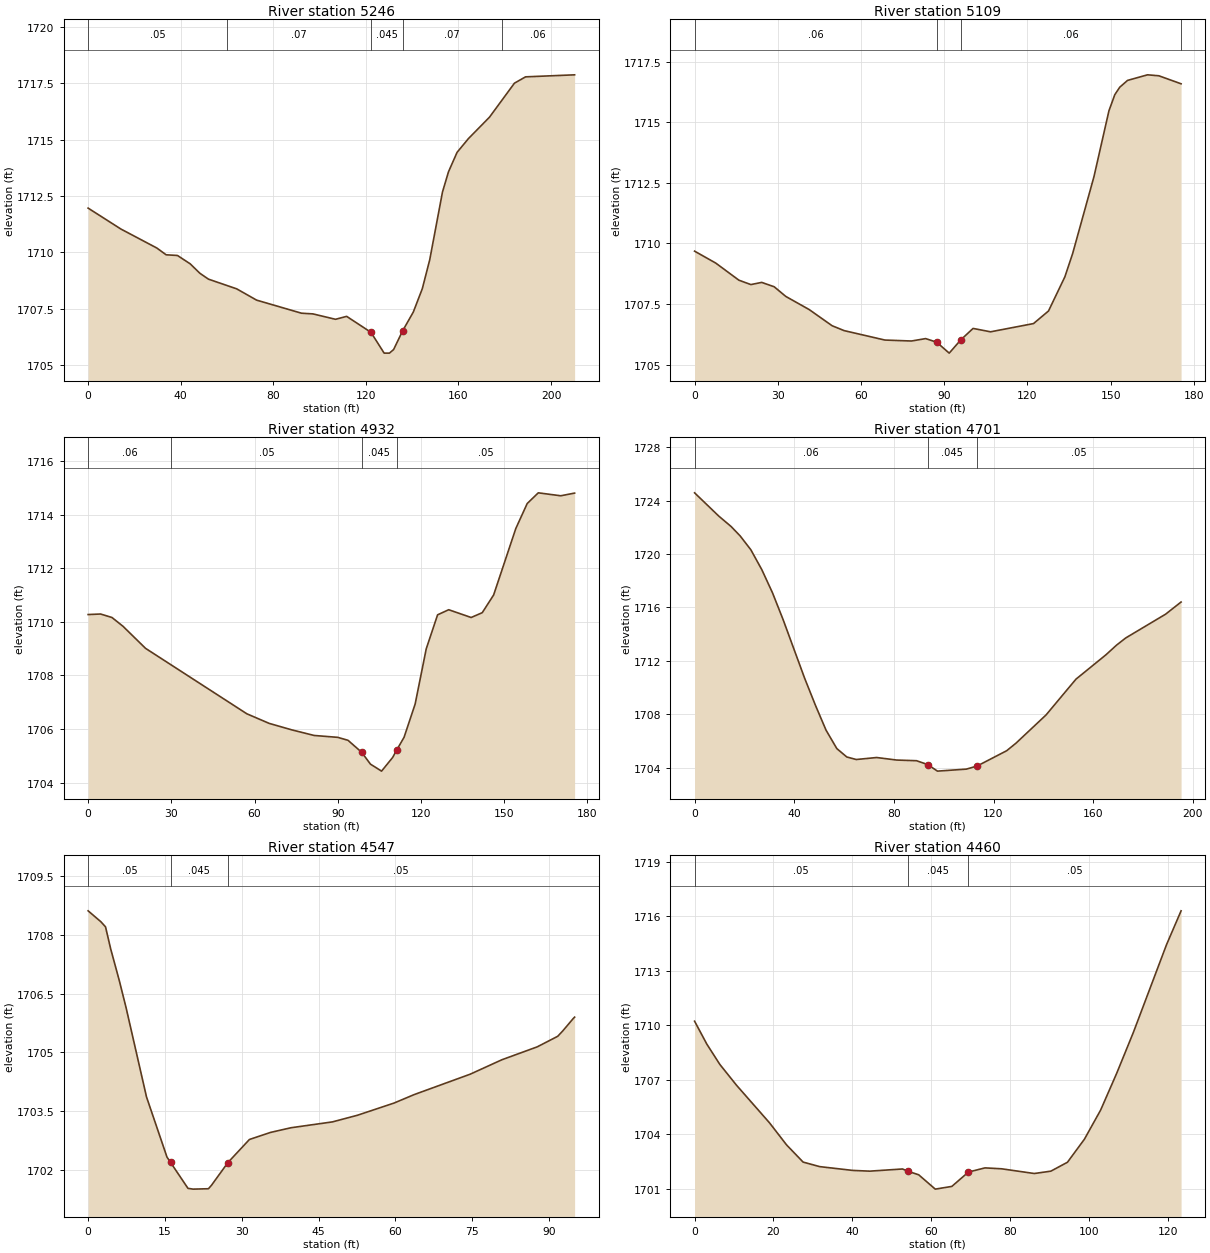
Type RM Length L Ch R = 1 ,5246    ,139.4,137.5,131.9
XS GIS Cut Line= 3
 2202625.9143296686041.5222511992202558.03930913686138.881443455
2202499.90748897686209.572775228
#Sta/Elev= 30
       0 1711.96    14.2 1711.03    29.7 1710.19    33.7 1709.89    38.6 1709.86
    44.1 1709.49    48.3 1709.07      52 1708.81    64.2 1708.38    72.8 1707.88
    92.2  1707.3    97.1 1707.27   106.9 1707.03   111.7 1707.16122.19961706.453
   127.9 1705.53   130.2 1705.53     132 1705.69 135.898 1706.52   140.5 1707.35
   144.4 1708.39   147.6 1709.67   153.1 1712.67   155.7 1713.57   159.4 1714.43
   164.3 1715.04   173.4 1715.99   184.2  1717.5     189 1717.78   210.2 1717.87
#Mann= 5 ,-1,0
       0     .05       0      60     .07       0122.1996    .045       0
 135.898     .07       0  178.68     .06       0
Bank Sta=122.1996,135.898
XS Rating Curve= 0 ,0
Exp/Cntr(USF)=0,0
Exp/Cntr=0.3,0.1

Type RM Length L Ch R = 1 ,5109    ,162.7,176.5,187.1
XS GIS Cut Line= 3
 2202471.4295545685993.9175988342202434.88146656686106.326003773
2202395.94380535686148.160952227
#Sta/Elev= 30
       0 1709.68     7.6 1709.19      16 1708.48    20.3  1708.3    24.2 1708.39
    28.7 1708.21    32.9 1707.81    41.3 1707.27    49.6  1706.6    53.9  1706.4
    68.6 1706.01    78.2 1705.97    83.3 1706.07    87.3 1705.92    91.8 1705.47
      96 1706.02   100.4 1706.49   106.7 1706.35   122.2 1706.69   127.6 1707.21
   133.5 1708.62   136.3 1709.58     144 1712.76   149.4 1715.48   151.5 1716.14
   153.3 1716.45   156.1 1716.73   163.3 1716.96   167.4 1716.92   175.4 1716.59
#Mann= 4 ,-1,0
       0     .06       0    87.3    .045       0      96     .06       0
  175.35     .05       0
Bank Sta=87.3,96
XS Rating Curve= 0 ,0
Exp/Cntr(USF)=0,0
Exp/Cntr=0.3,0.1

Type RM Length L Ch R = 1 ,4932    ,242.3,231.8,212.5
XS GIS Cut Line= 3
2202424.60979385685988.8823280512202335.85015169686003.624413945
2202251.21803991 686015.06977417
#Sta/Elev= 29
       0 1710.27     4.5 1710.29     8.6 1710.16    12.6 1709.83    20.7 1709.01
    57.2 1706.57    65.3 1706.21    73.4 1705.97    81.5 1705.76      90 1705.69
    93.7 1705.58    98.61705.135   101.8 1704.69   105.8 1704.43   109.8 1704.94
   111.21705.207   113.9 1705.69   117.9 1706.93   121.9 1708.99     126 1710.26
     130 1710.45   138.1 1710.16   142.1 1710.34   146.2    1711   154.2 1713.48
   158.3 1714.41   162.3 1714.81   170.4  1714.7   175.4  1714.8
#Mann= 4 ,-1,0
       0     .06       0      30     .05       0    98.6    .045       0
   111.2     .05       0
Bank Sta=98.6,111.2
XS Rating Curve= 0 ,0
Exp/Cntr(USF)=0,0
Exp/Cntr=0.3,0.1

Type RM Length L Ch R = 1 ,4701    ,151.8,153.5,154.2
XS GIS Cut Line= 4
2202245.66093342685824.1876535622202224.75080445685875.977195499
2202223.45746118685892.3247334342202224.78779774686015.318217734
#Sta/Elev= 30
       0 1724.58     9.7 1722.84    14.7 1722.05    18.3 1721.35    22.6 1720.31
      27 1718.82    31.3 1717.08    35.6 1715.05    44.2 1710.68    48.5 1708.67
    52.8 1706.79    57.1 1705.42    61.1 1704.79    64.9  1704.6    73.1 1704.75
    81.1 1704.56    89.1 1704.51    93.6 1704.22    97.5 1703.73   109.1 1703.88
   113.4 1704.11   125.3 1705.26     129 1705.82   141.1 1707.94   153.1 1710.62
   165.1 1712.44   169.4 1713.17   173.1 1713.71   189.1 1715.49   195.3  1716.4
#Mann= 3 ,0,0
       0     .06       0    93.6    .045       0   113.4     .05       0
Bank Sta=93.6,113.4
XS Rating Curve= 0 ,0
Exp/Cntr(USF)=0,0
Exp/Cntr=0.3,0.1

Type RM Length L Ch R = 1 ,4547    ,85.9,86.6,89.6
XS GIS Cut Line= 3
2202095.61794404685841.8463658812202089.47540825685894.057920088
2202089.16828146685936.441417032
#Sta/Elev= 29
       0 1708.62     2.5 1708.34     3.4 1708.21     4.4 1707.65     6.1 1706.83
     7.4 1706.15    11.4 1703.86    15.4 1702.32    16.11702.183    19.5 1701.52
    20.5  1701.5    23.5 1701.51    24.1  1701.6    27.3 1702.18    30.61702.644
    31.5 1702.77    35.6 1702.95    39.6 1703.07    47.7 1703.22    52.6 1703.39
    59.7  1703.7    63.7 1703.92    74.6 1704.44    80.8 1704.81    87.7 1705.14
    91.7 1705.41    92.7 1705.55    94.7 1705.86      95  1705.9
#Mann= 3 ,-1,0
       0     .05       0    16.1    .045       0    27.3     .05       0
Bank Sta=16.1,27.3
XS Rating Curve= 0 ,0
Exp/Cntr(USF)=0,0
Exp/Cntr=0.3,0.1

Type RM Length L Ch R = 1 ,4460    ,125.6,140.6,109.6
XS GIS Cut Line= 3
2202026.02528856 685819.062108132202012.81883662685859.602844338
2201989.17007383 685936.69166849
#Sta/Elev= 27
       0 1710.23     3.1 1708.97     6.4 1707.85    10.6 1706.71      19 1704.63
    23.3 1703.42    27.5 1702.47    31.7 1702.22    40.1 1702.01    44.4 1701.97
    52.7 1702.09      54 1701.97    56.8 1701.77      61 1700.98    65.2 1701.13
    69.4 1701.92    73.6 1702.15    77.8  1702.1    86.1 1701.84    90.3 1701.97
    94.5 1702.46    98.8 1703.73   102.9 1705.33     107 1707.37   111.2 1709.61
   119.6 1714.44   123.3 1716.31
#Mann= 3 ,-1,0
       0     .05       0      54    .045       0    69.4     .05       0
Bank Sta=54,69.4
XS Rating Curve= 0 ,0
Exp/Cntr(USF)=0,0
Exp/Cntr=0.3,0.1

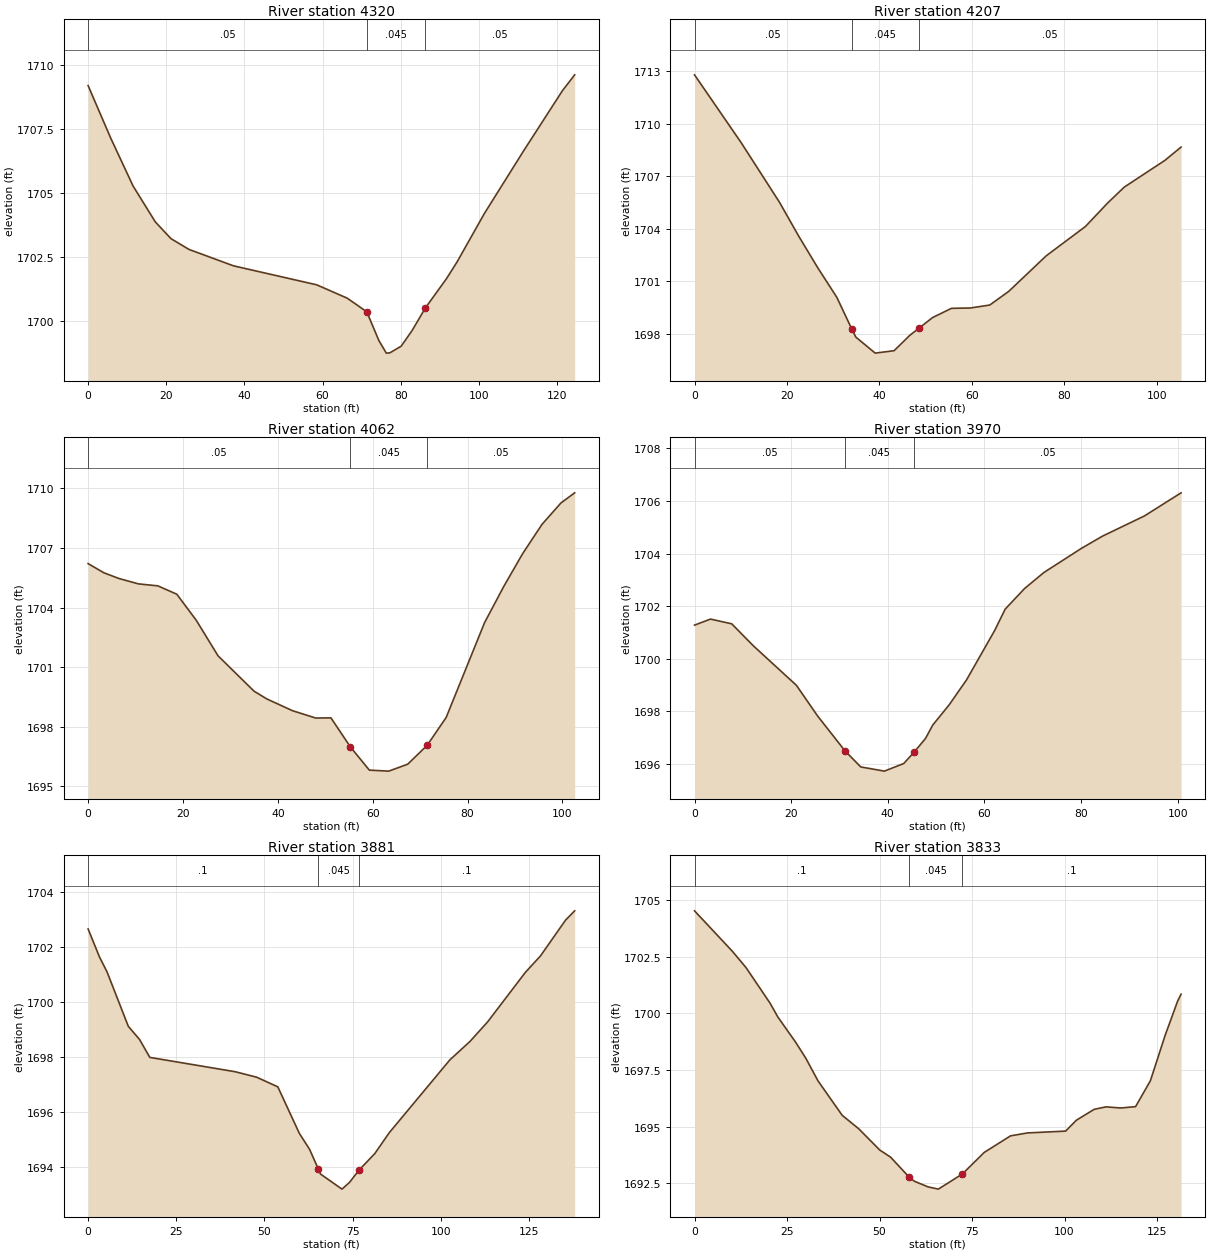
Type RM Length L Ch R = 1 ,4320    ,114.9,113,102.6
XS GIS Cut Line= 2
2201985.11128166685797.9731565542201885.68477644685872.964334225
#Sta/Elev= 22
       0 1709.18     5.8 1707.13    11.5 1705.27    17.2 1703.87    21.2 1703.22
    25.8  1702.8    37.2 1702.16    58.5 1701.42    66.3  1700.9    71.3 1700.37
    74.4 1699.25    76.3 1698.76    77.2 1698.77    80.1 1699.03    82.9 1699.64
    86.3 1700.52    91.7 1701.66    94.4 1702.31   101.4  1704.2   111.4 1706.63
   121.4 1708.99   124.5  1709.6
#Mann= 3 ,-1,0
       0     .05       0    71.3    .045       0    86.3     .05       0
Bank Sta=71.3,86.3
XS Rating Curve= 0 ,0
Exp/Cntr(USF)=0,0
Exp/Cntr=0.3,0.1

Type RM Length L Ch R = 1 ,4207    ,145.1,144.5,142.8
XS GIS Cut Line= 3
2201863.35594264 685739.412630172201843.13360259685816.089002845
2201835.55022507685840.945629152
#Sta/Elev= 23
       0  1712.8    10.1 1708.92    18.4 1705.51    22.5  1703.6    26.6  1701.8
    30.8 1700.08      341698.286    34.9 1697.81    39.1 1696.89    43.2 1697.03
    46.6 1697.91    48.6 1698.32    51.5 1698.92    55.6 1699.45    59.7 1699.47
    63.9 1699.64      68 1700.42    76.1 1702.45    84.6 1704.13    89.4 1705.47
      93 1706.38   101.8 1707.91   105.3 1708.67
#Mann= 3 ,-1,0
       0     .05       0      34    .045       0    48.6     .05       0
Bank Sta=34,48.6
XS Rating Curve= 0 ,0
Exp/Cntr(USF)=0,0
Exp/Cntr=0.3,0.1

Type RM Length L Ch R = 1 ,4062    ,88.6,92.6,95.4
XS GIS Cut Line= 3
2201721.63425986685714.7624537362201712.15503797685766.708589729
 2201705.3299982685816.000543592
#Sta/Elev= 25
       0 1706.21     3.3 1705.75     6.5 1705.46    10.6 1705.19    14.7 1705.09
    18.7 1704.67    22.8 1703.36    27.4 1701.57      35 1699.79    37.7  1699.4
    43.1 1698.81      48 1698.44    51.2 1698.45    55.3 1696.99    59.3 1695.82
    63.4 1695.77    67.4 1696.12    71.5 1697.07    75.5 1698.47    83.6 1703.24
    87.6 1705.04    91.6  1706.7    95.7 1708.18    99.7 1709.26   102.6 1709.77
#Mann= 3 ,-1,0
       0     .05       0    55.3    .045       0    71.5     .05       0
Bank Sta=55.3,71.5
XS Rating Curve= 0 ,0
Exp/Cntr(USF)=0,0
Exp/Cntr=0.3,0.1

Type RM Length L Ch R = 1 ,3970    ,83.9,88.9,91.9
XS GIS Cut Line= 3
2201645.80048469685702.2498808322201622.67118326685749.645990315
 2201618.8794945685797.421268674
#Sta/Elev= 23
       0 1701.28     3.3 1701.51     7.7 1701.33    12.2 1700.49    21.1 1698.99
    25.5 1697.82    31.1 1696.51    34.4 1695.89    39.3 1695.73    43.3 1696.02
    45.41696.442    47.8 1696.97    49.3 1697.48    52.7 1698.25    56.3  1699.2
    62.1 1701.07    64.3 1701.89    68.3 1702.67    72.3 1703.28      80 1704.19
    84.4 1704.66    93.1 1705.43   100.7 1706.31
#Mann= 3 ,-1,0
       0     .05       0    31.1    .045       0    45.4     .05       0
Bank Sta=31.1,45.4
XS Rating Curve= 0 ,0
Exp/Cntr(USF)=0,0
Exp/Cntr=0.3,0.1

Type RM Length L Ch R = 1 ,3881    ,49.2,48.2,56
XS GIS Cut Line= 3
2201597.18398835685681.6104700022201500.90895366685766.441960516
2201503.89422605685775.646550396
#Sta/Elev= 25
       0 1702.67     3.2 1701.66     5.4  1701.1    11.4 1699.13    14.6 1698.65
    17.5    1698    41.7 1697.48    47.8 1697.28    53.8 1696.93    59.9 1695.24
    62.8 1694.66    65.3 1693.94    65.9 1693.76      72 1693.21    74.1 1693.45
    76.9 1693.91    81.3  1694.5    85.4 1695.26   102.6 1697.91   108.3 1698.58
   113.3 1699.29     124 1701.09   128.3 1701.69   135.4 1702.99     138 1703.33
#Mann= 3 ,-1,0
       0      .1       0    65.3    .045       0    76.9      .1       0
Bank Sta=65.3,76.9
XS Rating Curve= 0 ,0
Exp/Cntr(USF)=0,0
Exp/Cntr=0.3,0.1

Type RM Length L Ch R = 1 ,3833    ,65.1,56.4,34.9
XS GIS Cut Line= 3
2201545.93681226685676.6350160132201466.82709383685738.330645478
2201468.81727543 685769.42723291
#Sta/Elev= 30
       0 1704.52    10.2 1702.74    13.9 1702.02    20.4 1700.45    22.5 1699.84
    27.3 1698.73    30.1 1698.01    33.4 1697.01    39.9  1695.5    44.4  1694.9
    50.1 1693.96      53 1693.65      58 1692.77    59.4 1692.59    63.1 1692.34
    65.9 1692.24    72.4 1692.91    78.3 1693.86    85.4 1694.59      90 1694.72
   100.3  1694.8   103.2 1695.28     108 1695.76   111.2 1695.87   115.2 1695.82
   119.2 1695.88   123.2 1697.02   127.2 1699.03   130.6 1700.55   131.5 1700.84
#Mann= 3 ,-1,0
       0      .1       0      58    .045       0    72.4      .1       0
Bank Sta=58,72.4
XS Rating Curve= 0 ,0
Exp/Cntr(USF)=0,0
Exp/Cntr=0.3,0.1

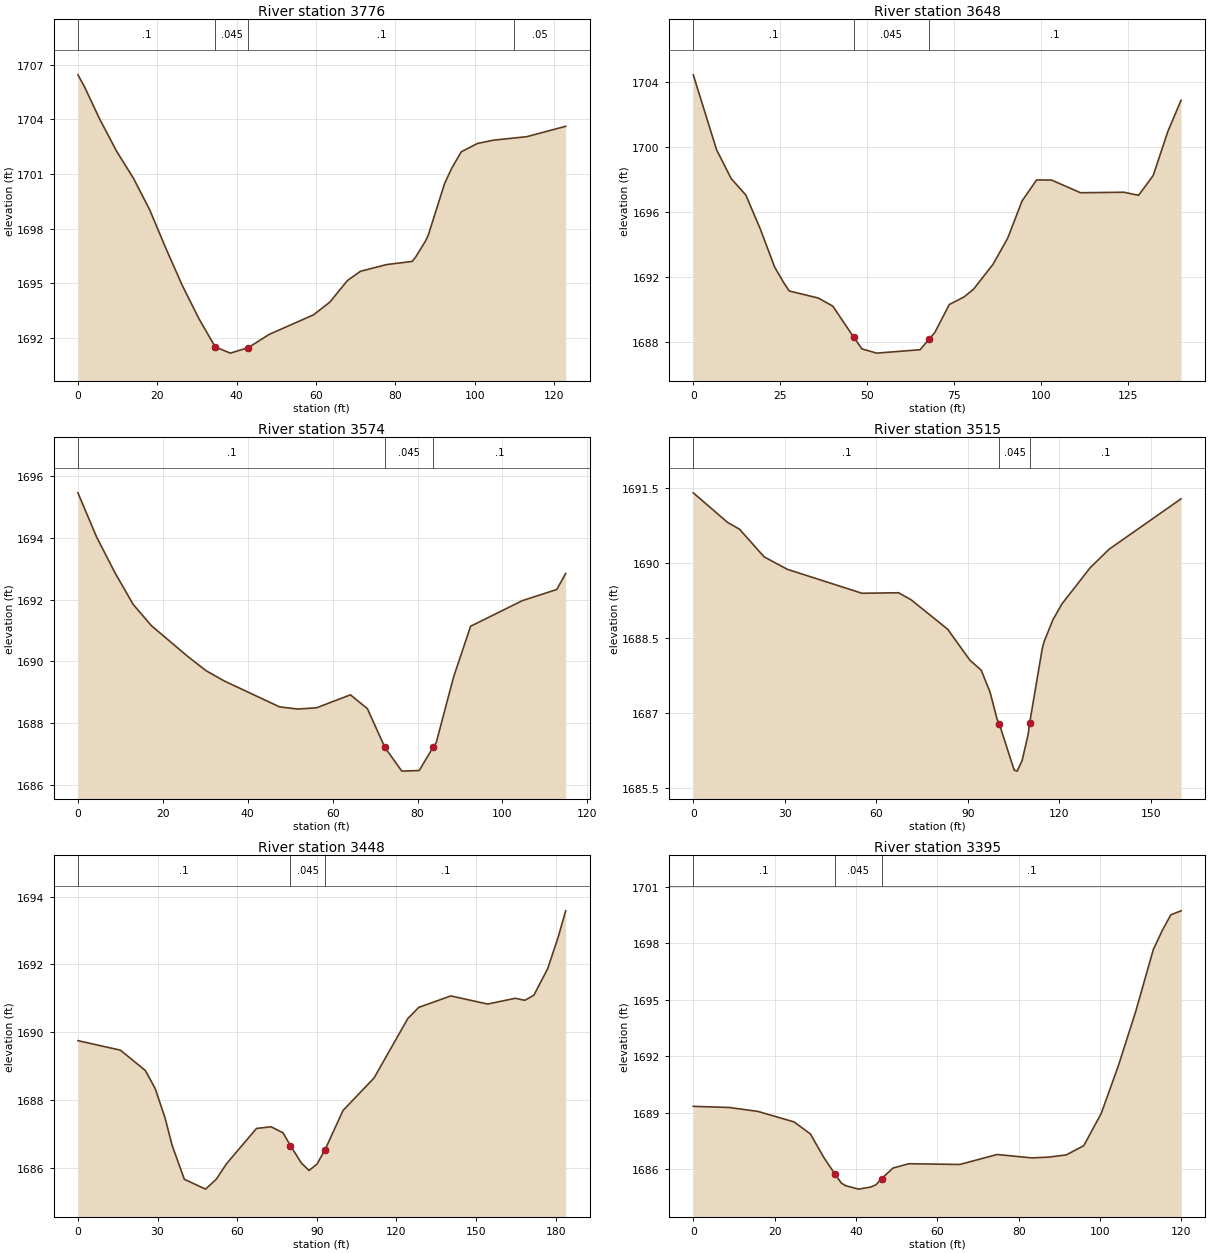
Type RM Length L Ch R = 1 ,3776    ,128.6,127.7,127.2
XS GIS Cut Line= 2
2201434.98271064685683.6677320582201465.61211229685802.717859215
#Sta/Elev= 29
       0 1706.45     1.6 1705.82     5.5 1704.01     9.8 1702.23      14 1700.76
    18.1 1699.02    22.2 1696.89    26.3 1694.87    30.5 1693.04    34.6 1691.49
    38.4 1691.15    42.9 1691.45    48.2 1692.18    59.4 1693.26    63.5 1693.96
    67.9 1695.14    71.2 1695.65    77.8 1696.02    84.2 1696.19    85.1 1696.43
    87.6 1697.32    88.3 1697.65    92.4 1700.48    94.2 1701.32    96.6 1702.22
   100.7 1702.68   104.8 1702.86   113.1 1703.05   122.9 1703.62
#Mann= 4 ,-1,0
       0      .1       0    34.6    .045       0    42.9      .1       0
     110     .05       0
Bank Sta=34.6,42.9
XS Rating Curve= 0 ,0
Exp/Cntr(USF)=0,0
Exp/Cntr=0.3,0.1

Type RM Length L Ch R = 1 ,3648    ,76.1,74.2,73.8
XS GIS Cut Line= 3
2201306.10805843685702.738868932 2201317.6663232 685741.45905592
2201347.13989837685836.814740294
#Sta/Elev= 30
       0 1704.45     6.7 1699.83    10.9 1698.05    15.1 1697.04    19.2 1694.98
    23.4 1692.59    26.1  1691.6    27.6 1691.12    35.9 1690.69    40.1 1690.19
    46.11688.278    48.5 1687.55    52.7 1687.29    65.2  1687.5    67.8 1688.16
    69.4 1688.55    73.6 1690.29    77.8 1690.75    80.6 1691.24    86.2 1692.78
    90.4 1694.39    94.5 1696.67    98.7 1697.97     103 1697.96   111.3 1697.18
   123.8 1697.21     128 1697.02   132.2 1698.24   136.4 1700.95   140.2 1702.88
#Mann= 3 ,-1,0
       0      .1       0    46.1    .045       0    67.8      .1       0
Bank Sta=46.1,67.8
XS Rating Curve= 0 ,0
Exp/Cntr(USF)=0,0
Exp/Cntr=0.3,0.1

Type RM Length L Ch R = 1 ,3574    ,68.3,59.7,50.8
XS GIS Cut Line= 3
2201243.83014597 685729.081320142201264.64651725685781.292874346
2201273.86032094685839.305712354
#Sta/Elev= 23
       0 1695.46     4.4 1694.03     8.7 1692.88      13 1691.85    17.3 1691.16
    25.9 1690.16    30.2  1689.7    34.6 1689.36    47.5 1688.53    51.8 1688.46
    56.2  1688.5    64.2 1688.92    68.2 1688.47    72.3 1687.22    76.3 1686.45
    80.4 1686.47    83.7 1687.23    84.4 1687.37    88.5  1689.5    92.5 1691.14
   104.7 1691.97   112.8 1692.33   114.9 1692.85
#Mann= 3 ,-1,0
       0      .1       0    72.3    .045       0    83.7      .1       0
Bank Sta=72.3,83.7
XS Rating Curve= 0 ,0
Exp/Cntr(USF)=0,0
Exp/Cntr=0.3,0.1

Type RM Length L Ch R = 1 ,3515    ,66.3,66.3,66.3
XS GIS Cut Line= 4
 2201108.9937185 685790.587810692201199.46986157685796.834493174
2201225.86713271685811.5444228922201262.25775333685825.655632823
#Sta/Elev= 26
       0 1691.41    11.2 1690.82    15.2 1690.68    23.2 1690.13    30.8 1689.88
    55.3  1689.4    67.3 1689.41    71.4 1689.27    83.4 1688.68    90.7 1688.06
    94.4 1687.86    97.3 1687.42    99.6 1686.88   100.3 1686.79   105.2 1685.86
   106.2 1685.84   107.8 1686.05   109.8 1686.58   110.31686.812   114.4 1688.29
     115 1688.43   117.9 1688.87   120.9 1689.19   130.1 1689.91   136.3 1690.28
   159.9 1691.29
#Mann= 3 ,-1,0
       0      .1       0   100.3    .045       0   110.3      .1       0
Bank Sta=100.3,110.3
XS Rating Curve= 0 ,0
Exp/Cntr(USF)=0,0
Exp/Cntr=0.3,0.1

Type RM Length L Ch R = 1 ,3448    ,53.8,53.8,53.8
XS GIS Cut Line= 4
2201068.23594152685817.7625342642201135.31201369685823.266868905
2201165.34218866685838.9644603662201246.85010672685852.178515917
#Sta/Elev= 30
       0 1689.75      16 1689.47    25.4 1688.87    29.1 1688.34    32.8 1687.48
    35.5 1686.66    40.1 1685.66    48.1 1685.37    52.1 1685.66    56.1 1686.13
    67.3 1687.16    72.8 1687.21    77.3 1687.03    80.1 1686.65    84.2 1686.14
    87.1 1685.92    90.1 1686.11    93.1 1686.53    99.9 1687.69   111.6 1688.65
   124.3  1690.4   128.4 1690.73   140.5 1691.07   154.4 1690.83   164.8    1691
   168.4 1690.94   171.8 1691.09     177 1691.87     181 1692.81   183.8 1693.58
#Mann= 3 ,-1,0
       0      .1       0    80.1    .045       0    93.1      .1       0
Bank Sta=80.1,93.1
XS Rating Curve= 0 ,0
Exp/Cntr(USF)=0,0
Exp/Cntr=0.3,0.1

Type RM Length L Ch R = 1 ,3395    ,44.3,43.7,42.5
XS GIS Cut Line= 5
2201067.40286803685821.9018609522201096.40928703 685822.24311294
2201105.01542671685846.3652058862201121.32068218685890.493510596
2201127.80446995 685907.55611001
#Sta/Elev= 28
       0 1689.33     8.8 1689.27    15.9 1689.06    24.8  1688.5    28.8 1687.86
    32.1 1686.61    34.81685.738    36.4 1685.25    37.4 1685.12    40.6 1684.93
    43.6 1685.04    44.9 1685.16    46.31685.488    49.1 1686.05      53 1686.28
    65.5 1686.24    74.7 1686.77    83.2 1686.59    87.3 1686.63    91.7 1686.75
      96 1687.24   100.3 1688.96   104.5 1691.49   108.8  1694.4   113.1 1697.67
   115.3 1698.68   117.4 1699.51   119.9 1699.72
#Mann= 3 ,-1,0
       0      .1       0    34.8    .045       0    46.3      .1       0
Bank Sta=34.8,46.3
XS Rating Curve= 0 ,0
Exp/Cntr(USF)=0,0
Exp/Cntr=0.3,0.1

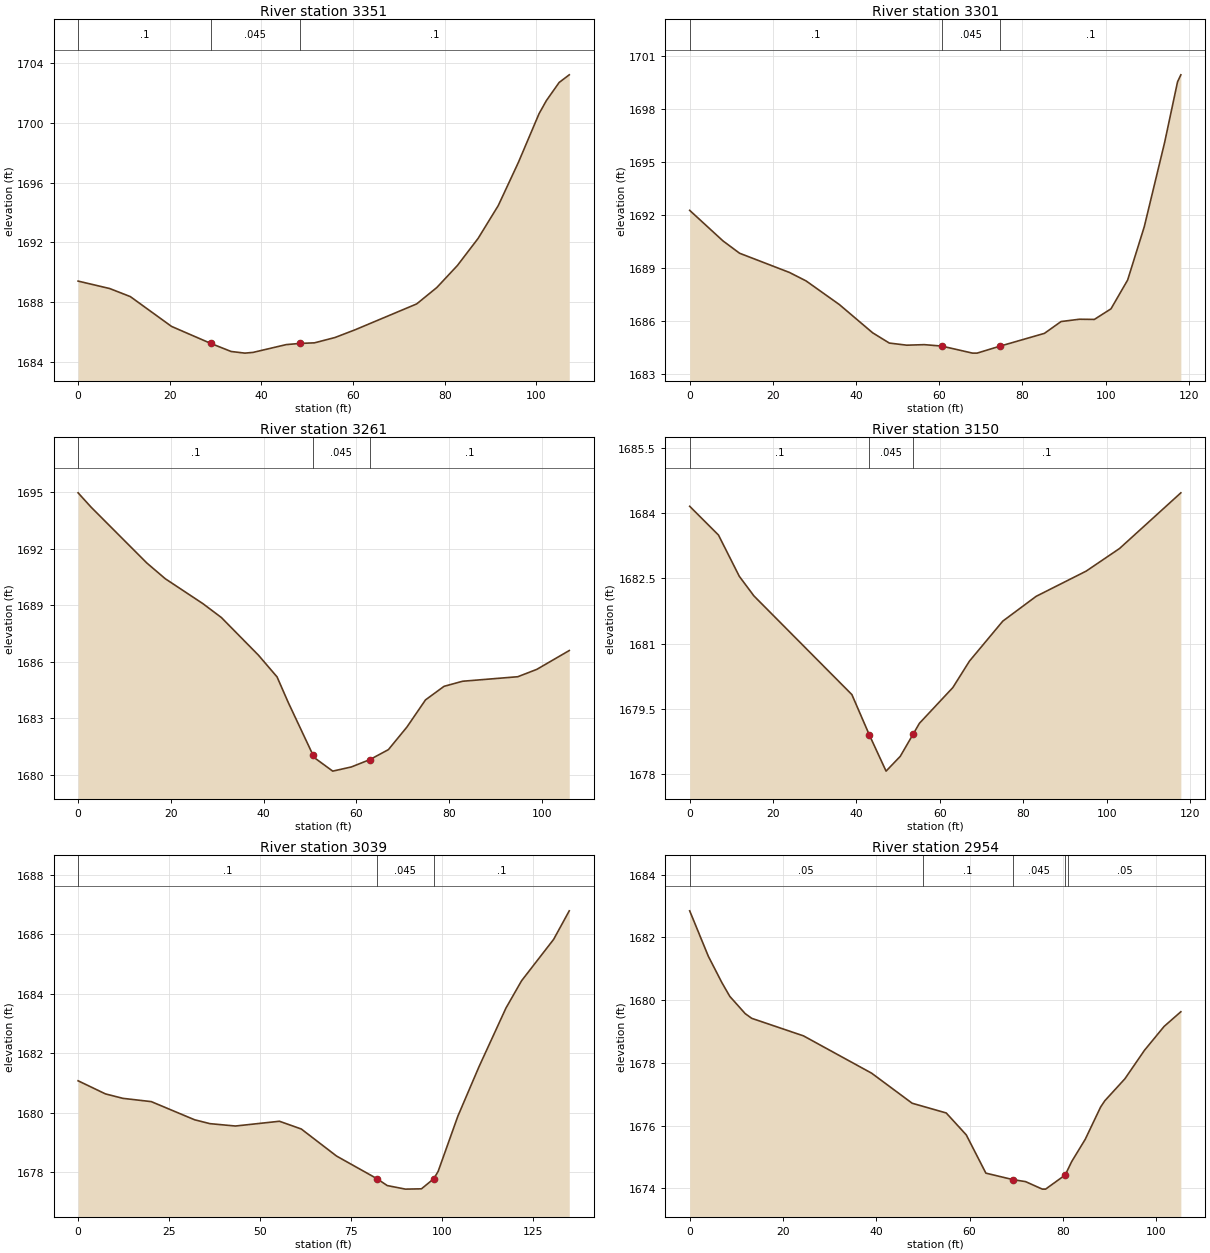
Type RM Length L Ch R = 1 ,3351    ,40,50,56.7
XS GIS Cut Line= 3
2201049.34797608685827.0603761582201058.19992676685843.972461325
2201096.92011375685923.146575017
#Sta/Elev= 23
       0  1689.4     6.9  1688.9    11.4 1688.36    20.4 1686.36    28.91685.228
    33.4 1684.68    36.4 1684.57    38.2 1684.62    45.4 1685.14    48.4 1685.22
    51.6 1685.26    56.1 1685.62    60.5 1686.14    73.9 1687.87    78.3 1688.97
    82.8 1690.45    87.3 1692.26    91.7 1694.46    96.1 1697.36   100.6 1700.62
   102.2  1701.5     105 1702.72   107.2 1703.23
#Mann= 3 ,-1,0
       0      .1       0    28.9    .045       0    48.4      .1       0
Bank Sta=28.9,48.4
XS Rating Curve= 0 ,0
Exp/Cntr(USF)=0,0
Exp/Cntr=0.3,0.1

Type RM Length L Ch R = 1 ,3301    ,43.4,39.6,39.2
XS GIS Cut Line= 5
2201027.76058688685813.2134112922201029.37263397685862.179341726
2201024.73799858685875.4787302392201021.91691617685883.538965701
2201019.10441206685929.889524397
#Sta/Elev= 24
       0 1692.27       8 1690.54      12 1689.84      24 1688.75      28 1688.27
      36 1686.93      44 1685.33      48 1684.75    52.2 1684.63    56.4 1684.66
    60.6 1684.58      68 1684.18    69.1 1684.1874.599811684.574    85.3  1685.3
    89.3 1685.97    93.7  1686.1    97.3 1686.09   101.3 1686.69   105.3 1688.32
   109.3 1691.34   114.2 1696.12   117.3 1699.55   118.1 1699.95
#Mann= 3 ,-1,0
       0      .1       0    60.6    .045       074.59981      .1       0
Bank Sta=60.6,74.59981
XS Rating Curve= 0 ,0
Exp/Cntr(USF)=0,0
Exp/Cntr=0.3,0.1

Type RM Length L Ch R = 1 ,3261    ,109.9,110.9,109.4
XS GIS Cut Line= 3
2200988.04301643685810.3390787592200985.93652268685876.904281411
2200983.26565468 685916.10469413
#Sta/Elev= 22
       0 1694.97     2.8 1694.21    14.8 1691.25    18.8 1690.41    26.9 1689.09
    30.9 1688.35    38.9 1686.35    42.9  1685.2    45.3 1683.85    50.61681.077
    50.9 1680.92    54.9  1680.2    58.9 1680.42    62.9 1680.81    66.9 1681.34
    70.9 1682.54    74.9 1683.98    78.9  1684.7    82.9 1684.97    94.8 1685.21
    98.9  1685.6   105.9  1686.6
#Mann= 3 ,-1,0
       0      .1       0    50.6    .045       0    62.9      .1       0
Bank Sta=50.6,62.9
XS Rating Curve= 0 ,0
Exp/Cntr(USF)=0,0
Exp/Cntr=0.3,0.1

Type RM Length L Ch R = 1 ,3150    ,104.5,111.1,117.9
XS GIS Cut Line= 4
2200882.94174099685822.3252352312200879.77300288685842.866913299
2200880.81324671685874.0742281852200881.42506548 685939.86758675
#Sta/Elev= 17
       0 1684.16     6.9  1683.5    11.9 1682.55    15.4  1682.1    38.9 1679.83
    43.1  1678.9    47.1 1678.07    50.5 1678.41    53.61678.922    55.1 1679.17
    63.1 1679.99    67.1  1680.6    75.1 1681.52    83.1 1682.09    95.1 1682.67
   103.1 1683.19   117.8 1684.47
#Mann= 3 ,-1,0
       0      .1       0    43.1    .045       0    53.6      .1       0
Bank Sta=43.1,53.6
XS Rating Curve= 0 ,0
Exp/Cntr(USF)=0,0
Exp/Cntr=0.3,0.1

Type RM Length L Ch R = 1 ,3039    ,77.5,85,93.8
XS GIS Cut Line= 3
2200838.46492041685811.6752020712200786.22387529685845.800400899
2200749.14958521685908.152616041
#Sta/Elev= 22
       0 1681.08     7.5 1680.64    12.3 1680.49    20.1 1680.38      32 1679.77
    36.2 1679.64    43.2 1679.56    55.3 1679.72    61.3 1679.46      71 1678.55
    82.1 1677.79    84.9 1677.56    89.9 1677.44    94.3 1677.45    97.7 1677.79
    98.9 1678.04   104.3 1679.89   110.1 1681.55   117.5 1683.52   121.8 1684.44
   130.6 1685.83   134.9 1686.79
#Mann= 3 ,-1,0
       0      .1       0    82.1    .045       0    97.7      .1       0
Bank Sta=82.1,97.7
XS Rating Curve= 0 ,0
Exp/Cntr(USF)=0,0
Exp/Cntr=0.3,0.1

Type RM Length L Ch R = 1 ,2954    ,86.7,80.2,72.9
XS GIS Cut Line= 3
2200795.50927268685762.9610735562200751.84966392685789.604629667
2200700.80150599685807.740159457
#Sta/Elev= 25
       0 1682.85       4  1681.4     6.9 1680.56     8.6 1680.12    11.9 1679.57
    13.3 1679.42    24.4 1678.86      39 1677.67    47.7 1676.71      55  1676.4
    59.3  1675.7    63.5 1674.48    69.4 1674.27      72 1674.21    75.6 1673.97
    76.3 1673.97    80.5 1674.42    81.9 1674.85    84.8 1675.56    88.1 1676.59
      89 1676.79    93.3 1677.49    97.5  1678.4   101.7 1679.16   105.3 1679.63
#Mann= 5 ,-1,0
       0     .05       0      50      .1       0    69.4    .045       0
    80.5      .1       0   81.15     .05       0
Bank Sta=69.4,80.5
XS Rating Curve= 0 ,0
Exp/Cntr(USF)=0,0
Exp/Cntr=0.3,0.1

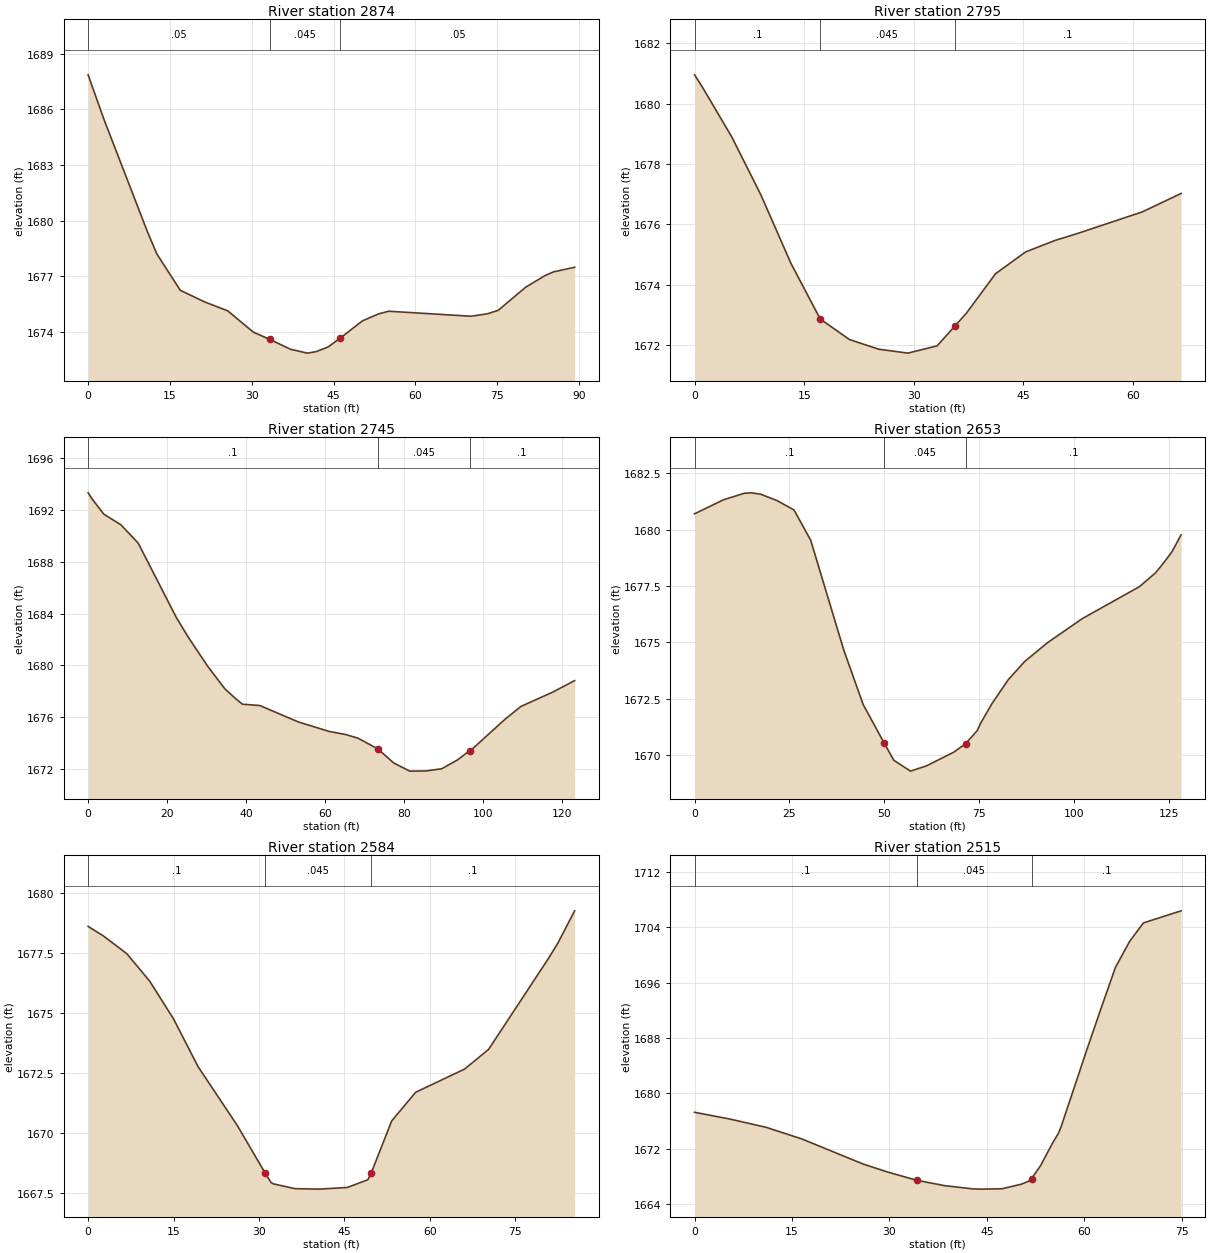
Type RM Length L Ch R = 1 ,2874    ,85.9,79.3,72.6
XS GIS Cut Line= 4
2200716.31915528685689.5047061932200706.24386095685714.133203439
2200694.15350776685731.1492560822200668.85332423685764.285779649
#Sta/Elev= 24
       0 1687.87     2.9 1685.47    10.9 1679.39    12.6 1678.21    16.9 1676.25
    21.3 1675.63    25.6 1675.14    30.3 1673.99    33.3  1673.6    37.1 1673.07
    40.2 1672.86    41.8 1672.94      44 1673.19    46.21673.665    50.3  1674.6
    53.2 1674.97    55.1 1675.12    70.2 1674.85    73.2 1674.98    75.2 1675.17
    80.2 1676.41    83.7 1677.03    85.3 1677.24    89.2 1677.49
#Mann= 3 ,-1,0
       0     .05       0    33.3    .045       0    46.2     .05       0
Bank Sta=33.3,46.2
XS Rating Curve= 0 ,0
Exp/Cntr(USF)=0,0
Exp/Cntr=0.3,0.1

Type RM Length L Ch R = 1 ,2795    ,50.3,50.3,51
XS GIS Cut Line= 2
 2200625.3599014685676.0715643432200619.83161919685742.410950864
#Sta/Elev= 21
       0 1680.95     1.1 1680.53     5.1 1678.89     9.1 1676.96    13.2  1674.7
    17.2 1672.86    21.2 1672.18    23.41672.004    25.2 1671.86    29.2 1671.73
    33.2 1671.97    35.61672.617   35.61 1672.62    37.2 1673.05    37.71673.214
    41.2 1674.36    45.3 1675.08    49.3 1675.46    52.5  1675.7    61.3 1676.41
    66.6 1677.02
#Mann= 3 ,-1,0
       0      .1       0    17.2    .045       0    35.6      .1       0
Bank Sta=17.2,35.6
XS Rating Curve= 0 ,0
Exp/Cntr(USF)=0,0
Exp/Cntr=0.3,0.1

Type RM Length L Ch R = 1 ,2745    ,99.9,91.6,88.2
XS GIS Cut Line= 3
 2200602.2199275685625.5791403612200575.84184914 685683.66066731
2200567.63235005685742.619797081
#Sta/Elev= 28
       0 1693.31     1.2 1692.76       4 1691.66     8.3 1690.85    12.7 1689.43
    22.4 1683.67    25.4 1682.17    30.3 1679.94    34.7 1678.18    37.5 1677.41
    39.1 1677.01    43.5 1676.91    53.3 1675.64    61.1 1674.91    65.3 1674.67
    68.4 1674.39    73.4 1673.57    77.4 1672.49    81.5 1671.85    85.5 1671.86
    89.6 1672.03    93.6 1672.71    96.7 1673.43    97.6 1673.62   105.7 1675.86
   109.7 1676.84   117.8 1677.95   123.3 1678.83
#Mann= 3 ,-1,0
       0      .1       0    73.4    .045       0    96.7      .1       0
Bank Sta=73.4,96.7
XS Rating Curve= 0 ,0
Exp/Cntr(USF)=0,0
Exp/Cntr=0.3,0.1

Type RM Length L Ch R = 1 ,2653    ,65.3,69,67.3
XS GIS Cut Line= 3
2200474.08748759685633.2476703162200498.08462495685687.102176549
2200523.67324843685751.432585606
#Sta/Elev= 28
       0  1680.7     7.6 1681.32    13.1 1681.61      15 1681.63    17.4 1681.57
    21.8 1681.28    26.2 1680.87    30.6 1679.53    39.3 1674.67    44.4 1672.26
      50 1670.53    52.5 1669.78    56.9  1669.3    61.2 1669.54    68.3 1670.14
    71.4 1670.51    74.5  1671.1    75.4 1671.43    78.4  1672.3    82.7 1673.36
      87 1674.16      93 1674.99   102.2 1676.06   117.2 1677.47   121.5 1678.09
   123.8 1678.57   125.8 1679.02   128.2 1679.77
#Mann= 3 ,-1,0
       0      .1       0      50    .045       0    71.4      .1       0
Bank Sta=50,71.4
XS Rating Curve= 0 ,0
Exp/Cntr(USF)=0,0
Exp/Cntr=0.3,0.1

Type RM Length L Ch R = 1 ,2584    ,60.6,69.2,81
XS GIS Cut Line= 3
2200431.32191809685670.5588296582200428.86490377685682.536774446
2200453.74217372685751.333175283
#Sta/Elev= 22
       0 1678.62     2.7 1678.22     6.8 1677.48    10.8 1676.34      15 1674.76
    19.3 1672.77    26.2 1670.31    31.1 1668.32    32.1 1667.94    32.5 1667.88
    36.3 1667.68    40.6 1667.66    45.5 1667.73    49.1 1668.05    49.71668.336
    53.3 1670.51    57.5  1671.7    66.1 1672.67    70.3 1673.49    80.8 1677.28
    82.5 1677.94    85.4 1679.27
#Mann= 3 ,-1,0
       0      .1       0    31.1    .045       0    49.7      .1       0
Bank Sta=31.1,49.7
XS Rating Curve= 0 ,0
Exp/Cntr(USF)=0,0
Exp/Cntr=0.3,0.1

Type RM Length L Ch R = 1 ,2515    ,38,50.3,61.1
XS GIS Cut Line= 3
2200392.31681583685665.3376742372200380.33887104685677.622745815
2200356.99723504  685730.4485536
#Sta/Elev= 24
       0 1677.28     5.4 1676.31      11 1675.11    16.5 1673.43      26 1669.78
    29.8 1668.62    34.2 1667.45    38.5 1666.67    42.9  1666.2    44.2 1666.17
    47.3 1666.22    50.3 1666.88    51.7 1667.43    51.91667.704    53.3 1669.62
    55.1 1672.81      56 1674.22    56.4 1675.11    60.4 1686.35    62.4 1691.82
    64.8 1698.25      67 1702.02    69.1 1704.66    74.9 1706.41
#Mann= 3 ,-1,0
       0      .1       0    34.2    .045       0    51.9      .1       0
Bank Sta=34.2,51.9
XS Rating Curve= 0 ,0
Exp/Cntr(USF)=0,0
Exp/Cntr=0.3,0.1