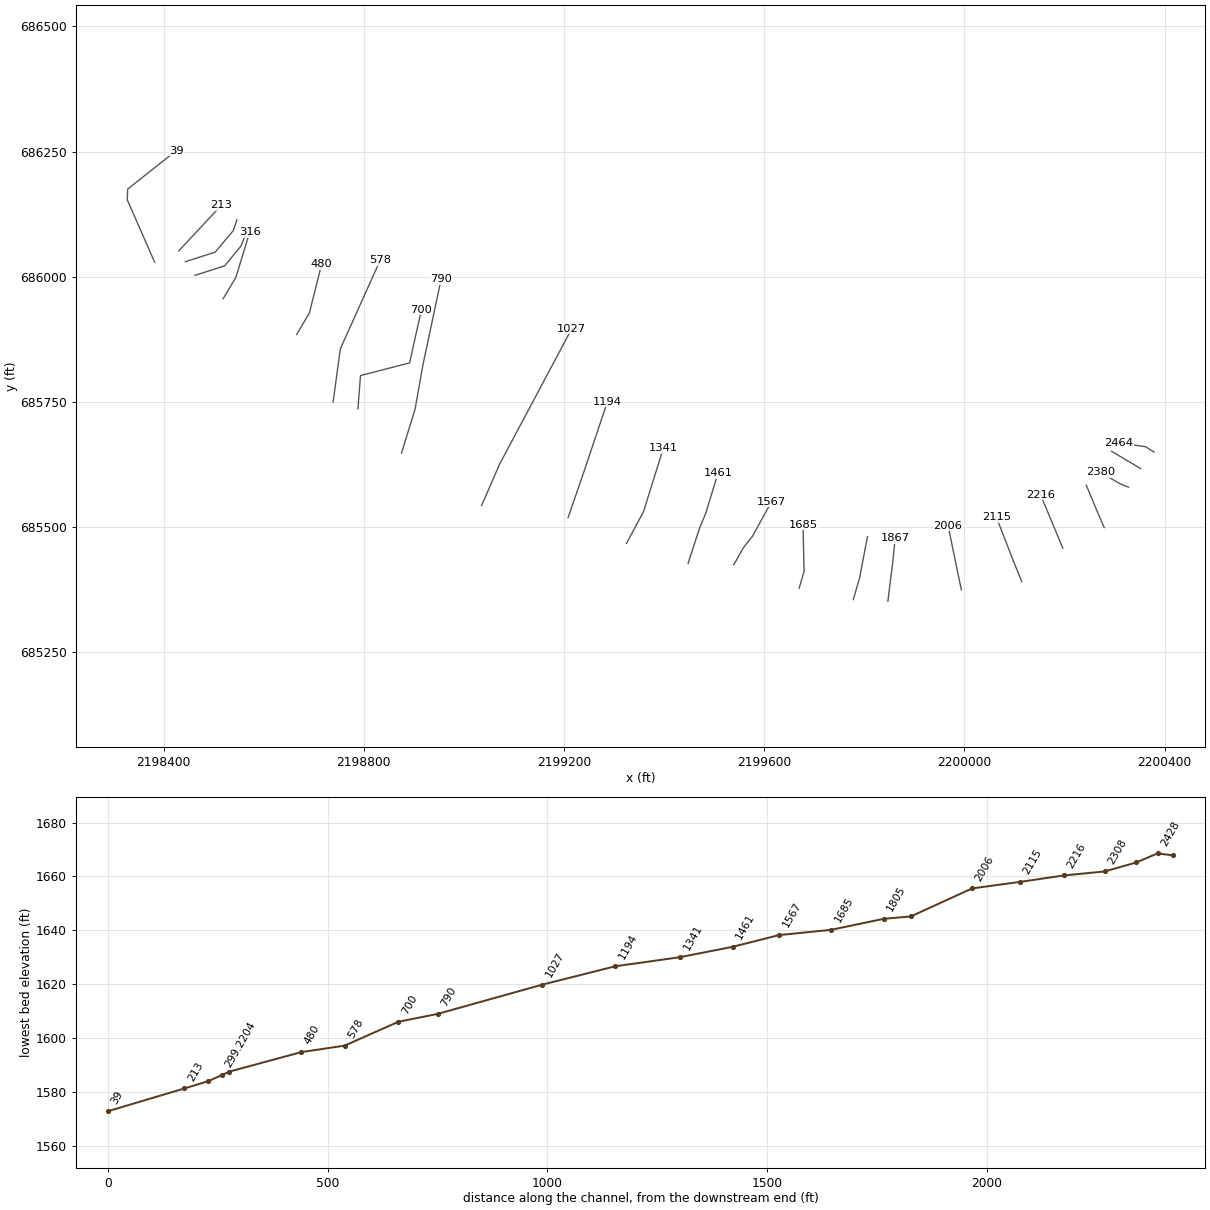
HEC-RAS study LAURELRN5.prj: LAURELRN5

--- LAURELRN5.g01 (geometry) --- (continued)

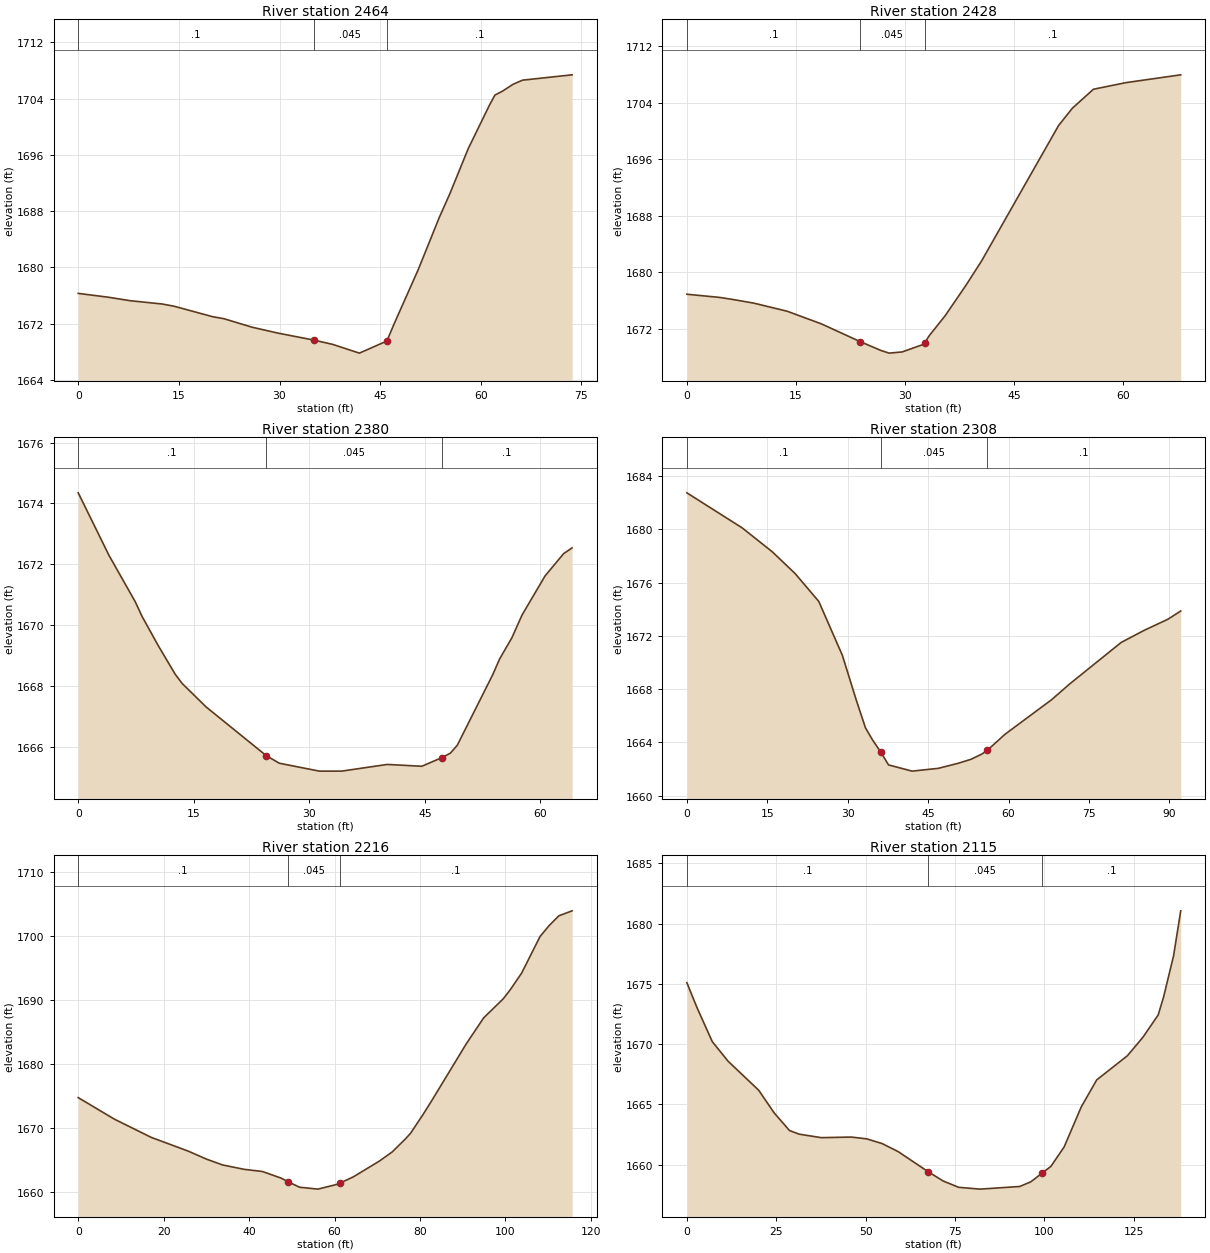
Type RM Length L Ch R = 1 ,2464    ,40.4,36.2,32.4
XS GIS Cut Line= 3
2200378.74808909685649.4743017182200361.88682835685660.254452028
2200308.81531913685667.717633011
#Sta/Elev= 24
       0 1676.29     4.5 1675.74     7.8 1675.24    12.5 1674.78    14.3 1674.46
      20 1672.98    21.7 1672.69    25.9 1671.48    29.8 1670.63    35.11669.649
    37.9 1669.04    41.9 1667.79      46 1669.51    47.1    1672    50.7 1679.73
    53.8 1687.07    55.4  1690.5    58.1 1696.83    61.3 1703.09    62.1  1704.5
    63.2 1705.04    64.8 1706.03    66.2 1706.62    73.6 1707.38
#Mann= 3 ,-1,0
       0      .1       0    35.1    .045       0      46      .1       0
Bank Sta=35.1,46
XS Rating Curve= 0 ,0
Exp/Cntr(USF)=0,0
Exp/Cntr=0.3,0.1

Type RM Length L Ch R = 1 ,2428    ,47.2,48.1,50.3
XS GIS Cut Line= 2
2200352.06167805685616.4259424982200293.73830073685651.254120421
#Sta/Elev= 21
       0 1676.88     4.5 1676.43     6.3 1676.14     9.2 1675.62    13.8 1674.47
    18.5 1672.68    23.8 1670.18    26.7 1668.91    27.8 1668.54    29.6 1668.71
    32.5 1669.77    32.7    1670   33.36 1671.06    35.5 1673.82    38.4 1678.19
    40.5 1681.56    51.1 1700.76      53 1703.22    55.9 1705.91    60.4 1706.85
    67.9 1707.95
#Mann= 3 ,-1,0
       0      .1       0    23.8    .045       0    32.7      .1       0
Bank Sta=23.8,32.7
XS Rating Curve= 0 ,0
Exp/Cntr(USF)=0,0
Exp/Cntr=0.3,0.1

Type RM Length L Ch R = 1 ,2380    ,78.3,72.3,60.7
XS GIS Cut Line= 3
2200327.88404293685579.3207265582200311.09188571685586.037589443
2200271.23849926685609.098818682
#Sta/Elev= 24
       0 1674.35       4 1672.29     7.4 1670.77     8.3 1670.28    10.4 1669.32
    12.6 1668.38    13.5 1668.08    16.6 1667.31    24.4 1665.71    26.1 1665.46
    31.3  1665.2    34.2  1665.2    40.1 1665.42    44.6 1665.36    47.21665.644
    48.3 1665.79    49.2 1666.05    53.8 1668.37    54.7 1668.89    56.3 1669.59
    57.6 1670.33    60.6 1671.62      63 1672.35    64.1 1672.54
#Mann= 3 ,-1,0
       0      .1       0    24.4    .045       0    47.2      .1       0
Bank Sta=24.4,47.2
XS Rating Curve= 0 ,0
Exp/Cntr(USF)=0,0
Exp/Cntr=0.3,0.1

Type RM Length L Ch R = 1 ,2308    ,92.1,92,91.8
XS GIS Cut Line= 3
2200279.15854841685498.619886612 2200267.7948572685524.725663715
2200243.22471404685583.386880499
#Sta/Elev= 24
       0 1682.75    10.3 1680.12    15.9 1678.33    20.2 1676.68    24.6 1674.59
      29 1670.54    31.6 1667.17    33.3  1665.1    34.6  1664.2    36.21663.248
    37.6 1662.31      42 1661.84    46.9 1662.05    50.6 1662.43      53 1662.73
      55 1663.12      56 1663.39    59.3  1664.6      68  1667.2    71.3 1668.36
      81 1671.51    85.3 1672.42    89.7 1673.25    92.1 1673.87
#Mann= 3 ,-1,0
       0      .1       0    36.2    .045       0      56      .1       0
Bank Sta=36.2,56
XS Rating Curve= 0 ,0
Exp/Cntr(USF)=0,0
Exp/Cntr=0.3,0.1

Type RM Length L Ch R = 1 ,2216    ,101.1,100.6,100.1
XS GIS Cut Line= 2
2200196.50488788685457.3565450292200152.03446417685564.085561937
#Sta/Elev= 30
       0 1674.69     8.5 1671.31    17.1 1668.47    25.8 1666.31    30.1 1665.05
    33.8 1664.16    38.8 1663.48    43.1 1663.14    47.5  1662.1    49.1 1661.54
    51.8 1660.68    56.1 1660.38    60.5 1661.11    61.3 1661.34    64.4  1662.3
    70.5 1664.77    73.5  1666.2    76.6 1668.24    77.8 1669.12    80.8 1672.14
    82.7 1674.16    90.8 1683.07    94.9 1687.16    99.5 1690.15   101.1 1691.53
   103.8 1694.17   108.1 1699.88   110.2 1701.57   112.5 1703.12   115.6  1703.9
#Mann= 3 ,-1,0
       0      .1       0    49.1    .045       0    61.3      .1       0
Bank Sta=49.1,61.3
XS Rating Curve= 0 ,0
Exp/Cntr(USF)=0,0
Exp/Cntr=0.3,0.1

Type RM Length L Ch R = 1 ,2115    ,110.8,109.2,106.1
XS GIS Cut Line= 3
2200114.44525339685390.5572875162200095.90810834 685436.47885137
2200063.88940327685519.053406557
#Sta/Elev= 30
       0  1675.1     2.8 1673.05     7.1 1670.21    11.5 1668.59    20.1 1666.17
    24.4  1664.3    28.7 1662.83    31.4 1662.53    37.6 1662.24      46 1662.29
    50.3 1662.14    54.6 1661.75    59.1 1661.08    67.4 1659.43    71.7 1658.64
      76 1658.12      82 1657.97    93.1 1658.19    96.2 1658.58    99.3 1659.29
   101.8 1659.86   105.5 1661.47   110.3  1664.8   114.6 1667.03   123.2 1669.04
   127.5 1670.56   131.8 1672.42   133.3  1673.9   136.1 1677.33   138.1 1681.06
#Mann= 3 ,-1,0
       0      .1       0    67.4    .045       0    99.3      .1       0
Bank Sta=67.4,99.3
XS Rating Curve= 0 ,0
Exp/Cntr(USF)=0,0
Exp/Cntr=0.3,0.1

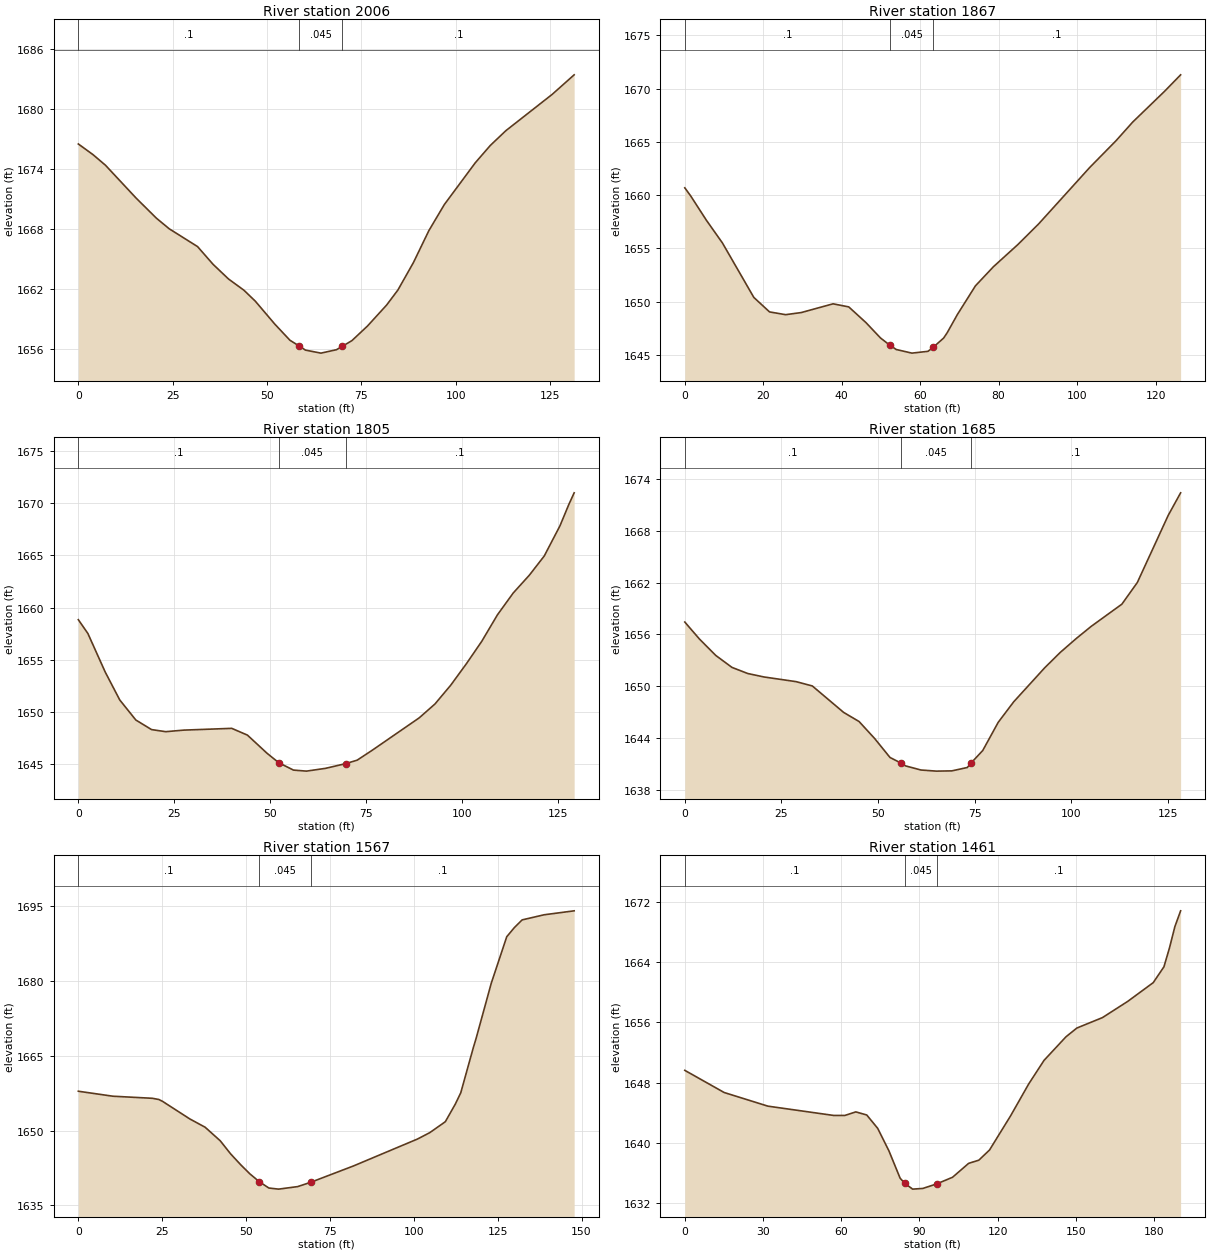
Type RM Length L Ch R = 1 ,2006    ,142.5,139.2,135
XS GIS Cut Line= 3
2199993.76958343685374.2142247592199984.55577975685418.235731247
2199967.15192835685502.866224339
#Sta/Elev= 30
       0 1676.47     3.9  1675.4     7.2 1674.34    15.3 1671.06    20.7 1669.04
    24.1 1667.98    31.6  1666.2    35.7 1664.43    39.8 1662.96    43.9 1661.83
    46.9 1660.74    52.1 1658.43    56.1 1656.82    58.6 1656.24    60.2 1655.84
    64.3 1655.54    68.4 1655.88      701656.231    72.5 1656.79    76.6 1658.24
    81.7 1660.35    84.7 1661.86    88.8  1664.6    92.9  1667.8      97 1670.41
   105.2 1674.59   109.2 1676.33   113.3  1677.8   125.6 1681.44   131.4 1683.39
#Mann= 3 ,-1,0
       0      .1       0    58.6    .045       0      70      .1       0
Bank Sta=58.6,70
XS Rating Curve= 0 ,0
Exp/Cntr(USF)=0,0
Exp/Cntr=0.3,0.1

Type RM Length L Ch R = 1 ,1867    ,62.3,61.7,60.5
XS GIS Cut Line= 4
2199847.03122847685351.691593533 2199852.1500083685394.348092067
2199856.58628414 685427.449534932199861.36381198685477.272325218
#Sta/Elev= 29
       0 1660.68     1.5 1659.92     5.5 1657.64     9.6  1655.5    17.6 1650.39
    21.6 1649.03    25.7 1648.77    29.7 1648.97    37.8 1649.79    41.8  1649.5
    46.2 1648.02    49.9 1646.58    52.31645.898    53.9  1645.5    57.9 1645.16
      62 1645.33    63.3  1645.7      66 1646.58    66.9 1647.08    69.5 1648.79
    74.1 1651.48    78.7 1653.28    84.9 1655.35    90.2 1657.29   103.2 1662.58
   109.9 1665.09   114.2 1666.86   122.3 1669.74   126.4 1671.29
#Mann= 3 ,-1,0
       0      .1       0    52.3    .045       0    63.3      .1       0
Bank Sta=52.3,63.3
XS Rating Curve= 0 ,0
Exp/Cntr(USF)=0,0
Exp/Cntr=0.3,0.1

Type RM Length L Ch R = 1 ,1805    ,117.3,120.4,122.9
XS GIS Cut Line= 3
2199777.84285195685354.798469873 2199790.5569432685398.719876008
2199806.16060064685480.783555892
#Sta/Elev= 30
       0 1658.83     2.5  1657.5       7 1653.81    10.8 1651.12      15 1649.19
    19.1 1648.27    22.8 1648.07    27.5 1648.22      40 1648.39    44.1 1647.74
    49.2    1646    52.3 1645.08    56.1 1644.38    59.5 1644.28    64.5 1644.55
    69.7    1645    72.7 1645.33    76.7  1646.3    88.9  1649.4      93 1650.73
    97.1 1652.53   101.2  1654.6   105.2 1656.75   109.3  1659.3   113.4 1661.39
   117.6  1663.1   121.5 1664.95   125.6 1667.85   127.9 1669.89   129.3 1671.02
#Mann= 3 ,-1,0
       0      .1       0    52.3    .045       0    69.7      .1       0
Bank Sta=52.3,69.7
XS Rating Curve= 0 ,0
Exp/Cntr(USF)=0,0
Exp/Cntr=0.3,0.1

Type RM Length L Ch R = 1 ,1685    ,126.2,117.8,109.4
XS GIS Cut Line= 3
2199669.65749368685377.5104601512199679.53981006 685411.31838461
 2199677.4593224685504.420207352
#Sta/Elev= 30
       0 1657.43     3.8 1655.46       8 1653.57    12.2 1652.18    16.3 1651.47
    20.5 1651.07    28.8 1650.53      33 1650.03    41.1 1646.97    45.1 1645.91
    49.1 1643.96    53.1 1641.75      56 1641.09    57.1 1640.78    61.1  1640.3
    65.1 1640.17    69.1  1640.2    73.1 1640.59    74.11641.119    77.1 1642.56
    81.1 1645.82    85.1 1648.19    93.1 1652.12    97.1 1653.89   101.1 1655.45
   105.1 1656.91   113.1  1659.5   117.1 1662.01   125.1 1669.79   128.3 1672.39
#Mann= 3 ,-1,0
       0      .1       0      56    .045       0    74.1      .1       0
Bank Sta=56,74.1
XS Rating Curve= 0 ,0
Exp/Cntr(USF)=0,0
Exp/Cntr=0.3,0.1

Type RM Length L Ch R = 1 ,1567    ,102.4,105.7,108.2
XS GIS Cut Line= 4
2199538.92852479685424.2529390582199558.19229941685458.285607555
2199576.81394821 685482.044262922199614.69937163685550.751725734
#Sta/Elev= 30
       0  1657.9    10.3  1656.9    22.1 1656.48      24 1656.24    25.1 1655.87
    33.2 1652.35    37.8 1650.67    42.3 1647.95    45.4 1645.32    48.3 1643.21
    51.1 1641.33      54  1639.7    56.8 1638.46    59.7 1638.24    65.4 1638.75
    69.3 1639.62      82 1642.89   101.1  1648.3   104.8  1649.6   109.4 1651.78
   112.4 1655.35     114 1657.59   117.7 1666.55   118.6 1668.58   123.1 1679.61
   127.7 1688.92     130 1690.78   132.3 1692.31   138.8 1693.33   147.8 1694.13
#Mann= 3 ,-1,0
       0      .1       0      54    .045       0    69.3      .1       0
Bank Sta=54,69.3
XS Rating Curve= 0 ,0
Exp/Cntr(USF)=0,0
Exp/Cntr=0.3,0.1

Type RM Length L Ch R = 1 ,1461    ,118.8,120.1,120.8
XS GIS Cut Line= 4
2199447.74665825685426.821442341 2199470.8631878685498.097408438
2199483.06357839685526.9930703692199507.46435958685607.258797955
#Sta/Elev= 30
       0 1649.64    15.1  1646.7    31.9 1644.89    57.1 1643.66    61.4 1643.66
    65.6 1644.13    69.8 1643.72      74 1641.95    78.3 1638.97    82.6 1635.34
    84.4 1634.65    87.4 1633.89    91.3 1633.98    96.6 1634.58   102.7 1635.46
   108.9 1637.31   112.8 1637.73   116.9 1639.08     125 1643.62   131.9 1647.82
   137.8 1650.96   146.2 1654.08   150.4 1655.25   160.2 1656.63   169.9 1658.78
   179.7 1661.27   183.8 1663.37   185.9 1665.84     188  1668.7   190.2 1670.79
#Mann= 3 ,-1,0
       0      .1       0    84.4    .045       0    96.6      .1       0
Bank Sta=84.4,96.6
XS Rating Curve= 0 ,0
Exp/Cntr(USF)=0,0
Exp/Cntr=0.3,0.1

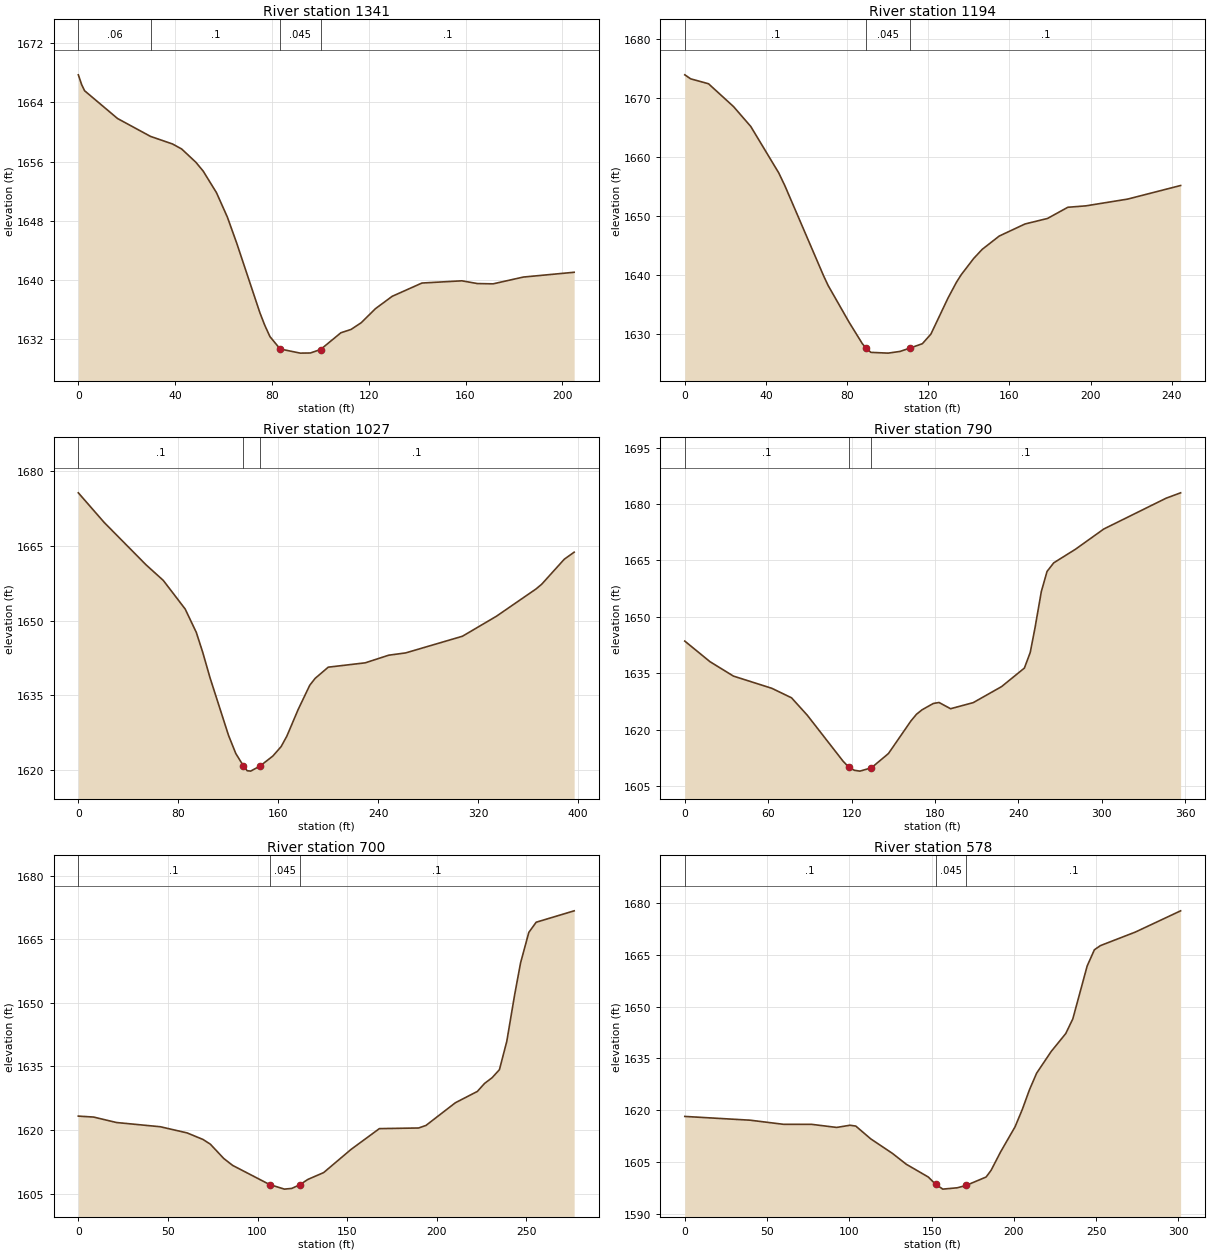
Type RM Length L Ch R = 1 ,1341    ,142.9,146.9,143.4
XS GIS Cut Line= 3
2199324.59326783685466.9186324782199358.68142868 685530.33846662
2199398.31882502685657.178134904
#Sta/Elev= 30
       0 1667.75     1.4  1666.4     2.6 1665.59    16.2 1661.83    29.8 1659.41
    38.9 1658.38    42.7  1657.7    48.6 1655.89    51.6  1654.7    57.1 1651.77
    61.6 1648.46    65.5 1644.89      75 1635.53      77 1633.84    79.2 1632.26
    83.4 1630.59    91.7 1630.03    95.9 1630.05   100.1 1630.52   108.5 1632.79
   112.7 1633.24   116.9 1634.15   122.8 1636.06   129.7 1637.73     142 1639.53
   158.5 1639.83   164.9 1639.46   171.4 1639.42   183.9 1640.34   204.9 1640.99
#Mann= 4 ,-1,0
       0     .06       0      30      .1       0    83.4    .045       0
   100.1      .1       0
Bank Sta=83.4,100.1
XS Rating Curve= 0 ,0
Exp/Cntr(USF)=0,0
Exp/Cntr=0.3,0.1

Type RM Length L Ch R = 1 ,1194    ,167.2,167,164.7
XS GIS Cut Line= 3
2199208.05932259685518.4472477182199240.56198759685612.784251005
2199286.54136734685749.929642338
#Sta/Elev= 30
       0 1673.97     2.9 1673.29    11.7 1672.45      24 1668.58    32.5  1665.2
    46.3 1657.31    49.4 1655.07    68.3  1639.9    70.6  1638.2    80.9 1631.97
    87.5 1628.28    89.21627.594    91.7  1626.8   100.2 1626.67   106.1 1626.96
   111.1 1627.54   117.1 1628.27   121.3  1629.9   129.7    1636   133.9 1638.72
   136.3 1640.02   142.4 1642.76   146.6 1644.31     155 1646.57   167.7 1648.62
   178.8 1649.56   188.8 1651.46   197.7  1651.7   218.3 1652.85   244.4 1655.16
#Mann= 3 ,-1,0
       0      .1       0    89.2    .045       0   111.1      .1       0
Bank Sta=89.2,111.1
XS Rating Curve= 0 ,0
Exp/Cntr(USF)=0,0
Exp/Cntr=0.3,0.1

Type RM Length L Ch R = 1 ,1027    ,232.3,237,240.1
XS GIS Cut Line= 3
2199035.31291868685542.7855234782199071.52486102685625.975120733
2199215.39392921685896.096636523
#Sta/Elev= 30
       0 1675.61    20.7 1669.67    54.1  1661.2      68 1658.05    85.5 1652.32
    94.4 1647.64    99.5 1643.68   105.4 1638.53   120.2 1626.99     126 1623.36
     132 1620.92   135.1  1619.9   137.9 1619.82   145.4 1620.84   155.7 1622.85
   162.3 1624.74   166.9 1626.85   175.9 1632.16   185.2 1637.03   189.5 1638.41
     200 1640.66   229.6 1641.53   248.4 1643.06     262 1643.52   307.4 1646.86
   334.6 1650.87   366.3 1656.34   370.8 1657.28   388.9  1662.3   396.8 1663.71
#Mann= 3 ,-1,0
       0      .1       0     132    .045       0   145.4      .1       0
Bank Sta=132,145.4
XS Rating Curve= 0 ,0
Exp/Cntr(USF)=0,0
Exp/Cntr=0.3,0.1

Type RM Length L Ch R = 1 ,790     ,102.4,89.9,71.9
XS GIS Cut Line= 4
2198875.40237843685647.739338095  2198902.448718685735.639941689
2198918.05237544685823.5405452832198954.46090947685995.180777153
#Sta/Elev= 30
       0 1643.56    18.2 1638.07      35 1634.26    62.6 1631.02    76.8 1628.49
    88.2 1623.83   113.8 1611.68   117.9 1610.08     122 1609.23     126 1609.01
   134.2 1609.88   146.5 1613.68   162.6  1622.3   166.7 1624.13   170.7 1625.31
   178.8 1626.99   182.9 1627.25   191.2 1625.59   207.5 1627.21   227.9 1631.47
   244.3 1636.39   248.5 1640.53   251.9 1646.99   256.5 1656.74   260.6 1662.07
   265.4 1664.35   281.1 1667.98   301.5 1673.36   346.3 1681.54   356.7 1682.96
#Mann= 3 ,-1,0
       0      .1       0   117.9    .045       0   134.2      .1       0
Bank Sta=117.9,134.2
XS Rating Curve= 0 ,0
Exp/Cntr(USF)=0,0
Exp/Cntr=0.3,0.1

Type RM Length L Ch R = 1 ,700     ,110.4,122.4,134.8
XS GIS Cut Line= 4
2198788.27689732685735.9639593782198793.34447811685802.406557244
2198891.47530492 685827.785219352198915.07599802685933.898681836
#Sta/Elev= 30
       0 1623.28     8.5 1623.06    21.3 1621.77    45.8 1620.77    60.7 1619.32
    69.6 1617.77    73.7 1616.65    81.1 1613.31    86.1 1611.66   106.7 1607.15
     115 1606.06   119.1 1606.23   123.8 1607.13     128 1608.33   136.9 1609.96
   152.2 1615.43     168 1620.33   189.9 1620.48     194 1621.08   210.4 1626.43
   222.7 1629.11   226.7 1630.99   230.9 1632.33     235 1634.24   239.1 1640.91
   243.5 1651.93   246.8 1659.43   251.4 1666.61   255.5 1669.01   276.7  1671.7
#Mann= 3 ,-1,0
       0      .1       0   106.7    .045       0   123.8      .1       0
Bank Sta=106.7,123.8
XS Rating Curve= 0 ,0
Exp/Cntr(USF)=0,0
Exp/Cntr=0.3,0.1

Type RM Length L Ch R = 1 ,578     ,94.8,98.3,100.6
XS GIS Cut Line= 3
2198738.64470425685749.7114155762198753.15610568685855.972322761
2198832.73475863686032.917798162
#Sta/Elev= 30
       0 1618.23    39.7 1617.14      60 1615.95    77.1 1615.94    92.3 1615.05
   100.4 1615.68   103.9 1615.44     113 1611.74   126.1 1607.57   134.6  1604.4
     148  1600.7   152.4 1598.61   156.8 1597.21   165.6  1597.6   170.9 1598.27
   183.1 1600.71   186.1 1602.63   191.9 1607.97   200.7 1615.24   205.1 1620.26
   209.4 1625.89   213.8 1630.74   222.6 1636.98   231.5  1642.2   235.8 1646.45
   244.5 1661.72   248.9 1666.42   252.6 1667.63   273.8 1671.54   301.3 1677.68
#Mann= 3 ,-1,0
       0      .1       0   152.4    .045       0   170.9      .1       0
Bank Sta=152.4,170.9
XS Rating Curve= 0 ,0
Exp/Cntr(USF)=0,0
Exp/Cntr=0.3,0.1

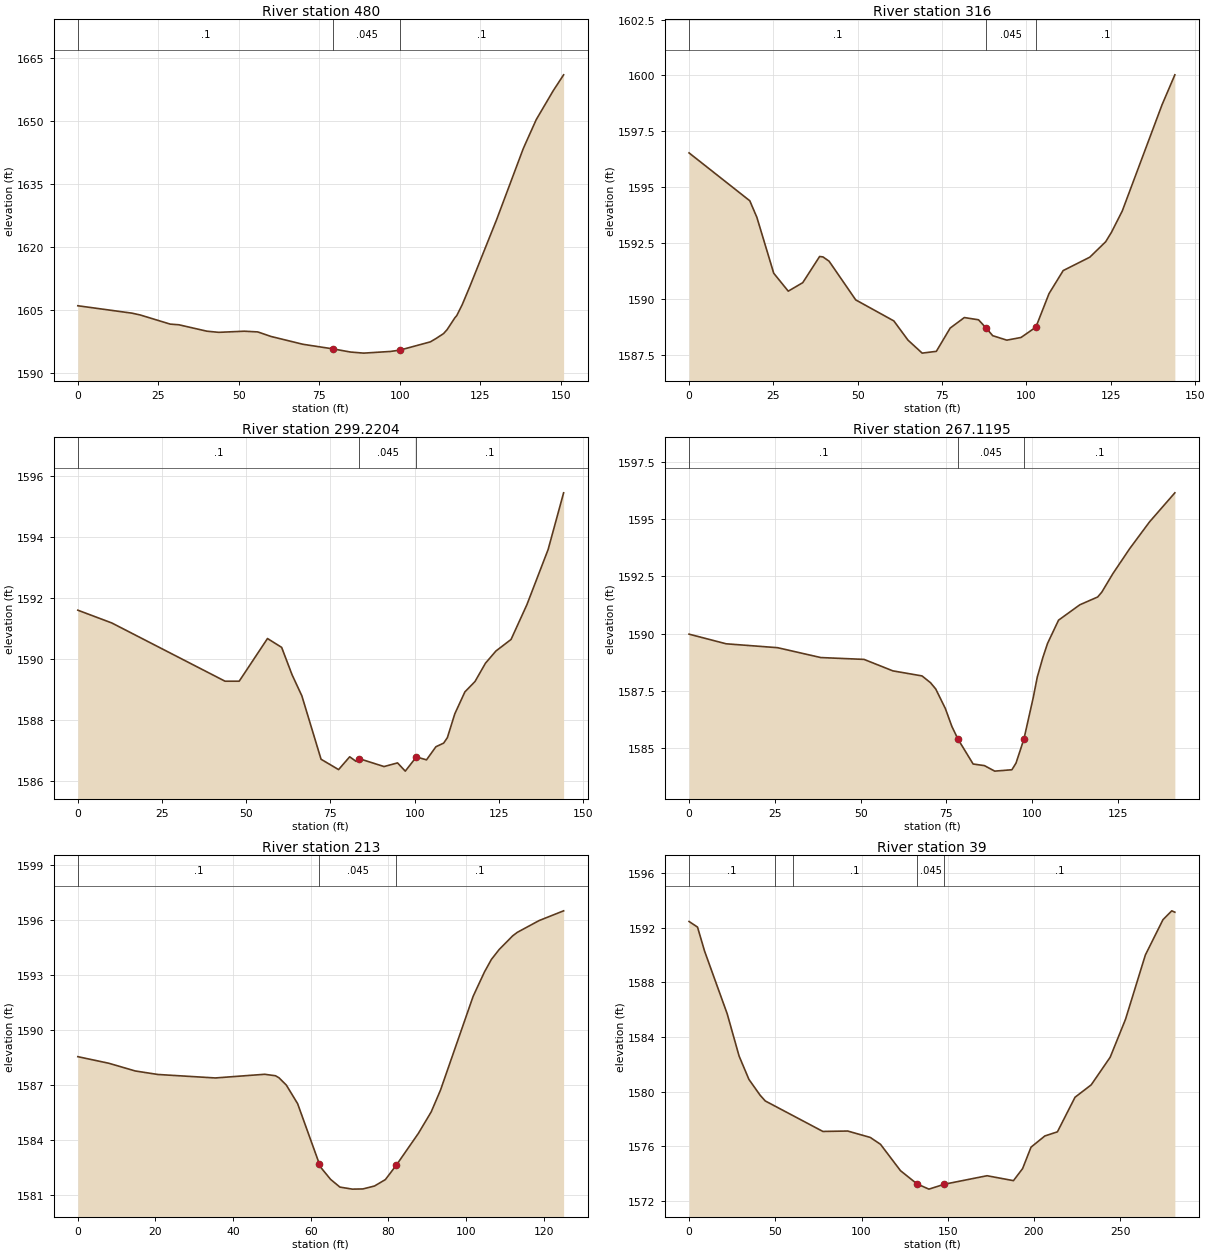
Type RM Length L Ch R = 1 ,480     ,163.5,163.8,161.4
XS GIS Cut Line= 3
2198665.85637211685884.4883664922198691.33231063685927.447792227
2198715.80919273686025.355320647
#Sta/Elev= 30
       0  1606.1    16.8 1604.34    19.4  1603.9    28.7 1601.73    31.4 1601.57
    40.1 1600.04    43.8 1599.77    51.7 1600.04    55.9 1599.87      60 1598.79
    69.9 1596.93    79.41595.812    84.7 1595.08    88.8 1594.82    97.1 1595.22
     1001595.531   109.5  1597.5   111.4 1598.36   113.6 1599.47   114.7  1600.4
   117.1 1603.21   117.7 1603.75   119.4 1606.35   121.8 1610.74   130.1 1626.63
   138.3 1643.39   139.1 1644.79   142.4 1650.43   147.7 1657.34   150.9 1661.09
#Mann= 3 ,-1,0
       0      .1       0    79.4    .045       0     100      .1       0
Bank Sta=79.4,100
XS Rating Curve= 0 ,0
Exp/Cntr(USF)=0,0
Exp/Cntr=0.3,0.1

Type RM Length L Ch R = 1 ,316     ,23,16.5,12.2
XS GIS Cut Line= 3
2198518.99507948685955.920899982  2198544.471018685998.880325717
2198571.94506934686088.795402837
#Sta/Elev= 30
       0 1596.54      18  1594.4    20.1 1593.66    25.1 1591.16    29.4 1590.36
    33.7 1590.74    38.7 1591.91    39.7 1591.89    41.5  1591.7    49.4 1589.97
    60.7 1589.03    64.9 1588.17    69.1 1587.59    73.3 1587.67    77.4 1588.71
    81.6 1589.18    85.8 1589.08   88.07 1588.71      90 1588.37    94.2 1588.17
    98.4 1588.29   102.8 1588.75   106.7 1590.25   110.9 1591.28   118.8 1591.88
   123.5 1592.57   125.2 1592.99   128.4 1593.94   140.2 1598.69     144 1600.03
#Mann= 3 ,-1,0
       0      .1       0   88.07    .045       0   102.8      .1       0
Bank Sta=88.07,102.8
XS Rating Curve= 0 ,0
Exp/Cntr(USF)=0,0
Exp/Cntr=0.3,0.1

Type RM Length L Ch R = 1 ,299.2204,32.4,32.1,32.3
XS GIS Cut Line= 4
2198462.55790918686002.572311966 2198521.9439785686021.606308545
2198554.46158212686060.8218232892198565.98217503 686089.48070285
#Sta/Elev= 30
       0 1591.61    10.1 1591.19    43.7 1589.28    47.9 1589.28    56.3 1590.68
    60.5 1590.39    63.6 1589.49    66.5  1588.8    72.2 1586.72    77.4 1586.38
    80.7  1586.8    82.6 1586.65    83.5 1586.74    90.9 1586.48    94.9  1586.6
    97.2 1586.33   100.51586.796   103.5  1586.7   106.3 1587.13   108.6 1587.25
   109.7 1587.43   111.9 1588.21   114.9 1588.93   117.9 1589.27     121 1589.87
   124.1 1590.27   128.6 1590.65   133.3 1591.79   139.6  1593.6   144.2 1595.46
#Mann= 3 ,-1,0
       0      .1       0    83.5    .045       0   100.5      .1       0
Bank Sta=83.5,100.5
XS Rating Curve= 0 ,0
Exp/Cntr(USF)=0,0
Exp/Cntr=0.3,0.1

Type RM Length L Ch R = 1 ,267.1195,54.5,53.9,53.2
XS GIS Cut Line= 4
2198443.59266339686029.8956901912198502.97873272 686048.92968677
2198539.52400615 686092.327198972198546.46913082686113.771813148
#Sta/Elev= 30
       0 1589.98    10.8 1589.56    25.8 1589.39    38.4 1588.96      51 1588.88
    59.4 1588.38    67.9 1588.16    70.4 1587.86    71.9 1587.59    74.7 1586.74
    76.6 1585.96    78.4  1585.4    82.8 1584.32    86.1 1584.25    89.1 1584.01
    94.1 1584.07    95.3 1584.36    97.61585.406   100.3  1587.2   101.5 1588.11
   103.1 1588.95   104.5 1589.58   107.7 1590.59   113.9 1591.26   119.1  1591.6
   120.3 1591.81   123.5 1592.61   128.4  1593.7   134.2 1594.87   141.6 1596.14
#Mann= 3 ,-1,0
       0      .1       0    78.4    .045       0    97.6      .1       0
Bank Sta=78.4,97.6
XS Rating Curve= 0 ,0
Exp/Cntr(USF)=0,0
Exp/Cntr=0.3,0.1

Type RM Length L Ch R = 1 ,213     ,174.1,174.1,174.1
XS GIS Cut Line= 2
2198430.07905877 686051.330787372198515.49838204686142.744449109
#Sta/Elev= 30
       0 1588.55       8 1588.19    14.8 1587.77    20.6 1587.58    35.4 1587.39
    48.1 1587.59    50.9 1587.51    51.8  1587.4    53.7    1587    56.6 1585.99
    62.2  1582.7    62.7 1582.48    65.1 1581.86    67.5 1581.44    70.7 1581.33
    73.4 1581.34    76.4  1581.5    79.2 1581.85      82 1582.63    87.7 1584.37
      91 1585.54    93.4 1586.73   101.8 1591.84   104.7 1593.16   106.5 1593.85
   108.5 1594.39     112 1595.14   113.2 1595.33   118.8 1595.97   125.1  1596.5
#Mann= 3 ,-1,0
       0      .1       0    62.2    .045       0      82      .1       0
Bank Sta=62.2,82
XS Rating Curve= 0 ,0
Exp/Cntr(USF)=0,0
Exp/Cntr=0.3,0.1

Type RM Length L Ch R = 1 ,39      ,,,
XS GIS Cut Line= 4
2198382.12751876686028.9008532752198327.39752488686153.563617111
2198328.21653434686174.9726667972198425.52453411686251.967040449
#Sta/Elev= 30
       0 1592.46     4.9 1592.05       9 1590.29    22.1 1585.71      29 1582.62
    34.7 1580.91    41.2 1579.75    44.2 1579.33    77.6  1577.1      92 1577.13
   105.1 1576.66     111 1576.16   122.6 1574.23   132.2 1573.26   139.1 1572.88
   148.1 1573.24   172.8 1573.86   188.1  1573.5   193.4 1574.38   198.3 1575.95
   206.3 1576.77   213.6 1577.07   223.8  1579.6   233.2 1580.51   244.2 1582.53
   253.1 1585.31   264.6 1590.01   274.8 1592.59   279.9 1593.24   281.7 1593.14
#Mann= 5 ,-1,0
       0      .1       0      50    .025       0      60      .1       0
   132.2    .045       0   148.1      .1       0
Bank Sta=132.2,148.1
XS Rating Curve= 0 ,0
Exp/Cntr(USF)=0,0
Exp/Cntr=0.3,0.1
LCMann Table=0

Chan Stop Cuts=-1
Use User Specified Reach Order=0
Composite Channel Slope=5